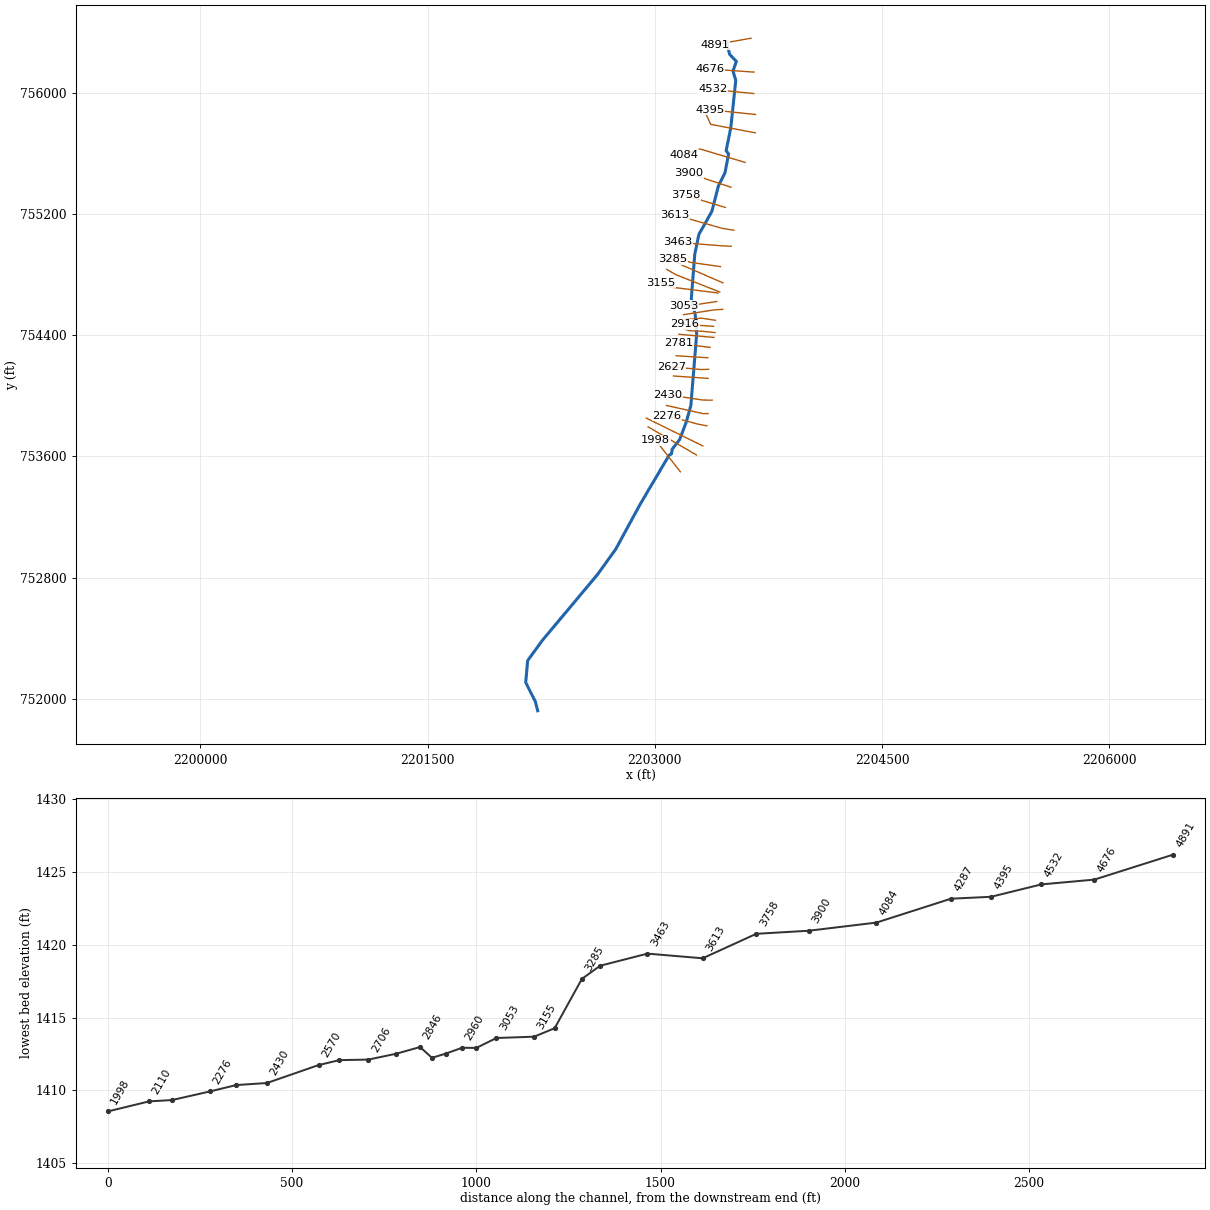
--- PECKSRNT3.prj (project) ---

Proj Title=PECKSRNT3
Current Plan=p01
Default Exp/Contr=0,0
English Units
Geom File=g01
Flow File=f01
Plan File=p01
BEGIN DESCRIPTION:
---------- MODELED AS PART OF WVEMD CTP PROGRAM, 2023----------
Stream Name: Pecks Run Tributary 3
Flood Zone:  AFH
Upshur County, WV
HEC-RAS Version: RAS 6.3
Vertical Datum: NAVD88
Projection: NAD 1983 StatePlane West Virginia S FIPS 4702 (US Feet)
Terrain: 1-meter LIDAR (FEMA Region III 3DEP collected 2016-2018)
Land Use: 2019 NLCD
Hydrologic Method:
WV SIR2010-5033 regression equations
Additional Model Notes:
None
END DESCRIPTION:
DSS Export Rating Curves= 0
DSS Export Rating Curve Sorted= 0
DSS Export Volume Flow Curves= 0
DXF OffsetX= 0
DXF OffsetY= 0
DXF ScaleX= 0
DXF ScaleY= 0

--- PECKSRNT3.p01 (plan) ---

Plan Title=Floodplain
Program Version=6.30
Short Identifier=Floodplain
Geom File=g01
Flow File=f01
Subcritical Flow
K Sum by GR= 0
Std Step Tol= 0.01
Critical Tol= 0.01
Num of Std Step Trials= 20
Max Error Tol= 0.3
Flow Tol Ratio= 0.001
Split Flow NTrial= 30
Split Flow Tol= 0.02
Split Flow Ratio= 0.02
Log Output Level= 0
Friction Slope Method= 1
Unsteady Friction Slope Method= 2
Unsteady Bridges Friction Slope Method= 1
Parabolic Critical Depth
Global Vel Dist= 0 , 0 , 0
Global Log Level= 0
CheckData=False
Encroach Param=-1 ,0,0, 0
Mapping Interval=1HOUR
Computation Time Step Use Courant=        0
Computation Time Step Use Time Series=    0
Computation Time Step Count To Double=0
Computation Time Step Max Doubling=0
Computation Time Step Max Halving=0
Computation Time Step Residence Courant=0
Run HTab= 0
Run UNet= 0
Run Sediment= 0
Run PostProcess= 0
Run WQNet= 0
Run RASMapper=-1
UNET Theta= 0
UNET Theta Warmup= 0
UNET ZTol= 0
UNET ZSATol= 0
UNET MxIter= 0
UNET Max Iter WO Improvement= 0
UNET MaxInSteps= 0
UNET DtIC= 0
UNET DtMin= 0
UNET MaxCRTS= 0
UNET WFStab= 0
UNET SFStab= 0
UNET WFX= 1
UNET SFX= 1
UNET Gravity=32.17405
UNET 1D Methodology=Finite Difference
UNET DSS MLevel= 1
UNET Pardiso=0
UNET DZMax Abort= 0
UNET Use Existing IB Tables= 0
UNET Froude Reduction=False
UNET Froude Limit= 0
UNET Froude Power= 0
UNET D1 Cores= 0
UNET WindReference=Eulerian
UNET WindDragFormulation=Hsu (1988)
UNET D2 Coriolis=0
UNET D2 Cores= 0
UNET D2 Theta= 1
UNET D2 Theta Warmup= 1
UNET D2 Z Tol= 0.01
UNET D2 Volume Tol= 0.01
UNET D2 Max Iterations= 20
UNET D2 Equation= 0
UNET D2 RampUpFraction=0.1
UNET D2 TimeSlices= 1
UNET D2 Turbulence Formulation=Non-Conservative (original)
UNET D2 Eddy Viscosity=0.3
UNET D2 Transverse Eddy Viscosity=0.1
UNET D2 Smagorinsky Mixing=0
UNET D2 BCVolumeCheck=0
UNET D2 Cores=0
UNET D2 SolverType=PARDISO (Direct)
UNET D2 Minimum Iterations= 3
UNET D2 Maximum Iterations= 30
UNET D2 Restart Number= 10
UNET D2 Relaxation Coeff=1.3
UNET D2 SOR Precondition Iterations= 10
UNET D2 ILUT Maximum Fill= 8
UNET D2 ILUT Tolerance=1E-08
UNET D2 Convergence Tolerance=0.00001
UNET D1D2 MaxIter= 0
UNET D1D2 ZTol=0.01
UNET D1D2 QTol=0.1
UNET D1D2 MinQTol=1
Write IC File= 0
Write IC File at Fixed DateTime=0
Write IC File at Sim End=0
Echo Input=False
Echo Parameters=False
Echo Output=False
Write Detailed= 0
HDF Write Warmup=0
HDF Write Time Slices=0
HDF Flush=0
HDF Compression= 1
HDF Chunk Size= 1
HDF Spatial Parts= 1
HDF Use Max Rows=0
HDF Fixed Rows= 1
Calibration Method= 0
Calibration Iterations= 20
Calibration Max Change=0.05
Calibration Tolerance=0.2
Calibration Maximum=1.5
Calibration Minimum=0.5
Calibration Optimization Method= 1
WQ AD Non Conservative
WQ ULTIMATE=-1
WQ Max Comp Step=1HOUR
WQ Output Interval=15MIN
WQ Output Selected Increments= 0
WQ Output face flow=0
WQ Output face velocity=0
WQ Output face area=0
WQ Output face dispersion=0
WQ Output cell volume=0
WQ Output cell surface area=0
WQ Output cell continuity=0
WQ Output cumulative cell continuity=0
WQ Output face conc=0
WQ Output face dconc_dx=0
WQ Output face courant=0
WQ Output face peclet=0
WQ Output face adv mass=0
WQ Output face disp mass=0
WQ Output cell mass=0
WQ Output cell source sink temp=0
WQ Output nsm pathways=0
WQ Output nsm derived pathways=0
WQ Create Restart=0
WQ Fixed Restart=0
WQ System Summary=0
WQ Write To DSS=0
Sorting and Armoring Iterations= 10
XS Update Threshold= 0.02
Bed Roughness Predictor= 0
Hydraulics Update Threshold= 0.02
Energy Slope Method= 1
Volume Change Method= 1
Sediment Retention Method= 0
Sediment TS Multiplier= 1
Warm Up Method= 0
XS Weighting Method= 0
Number of US Weighted Cross Sections= 1
Number of DS Weighted Cross Sections= 1
Upstream XS Weight=0
Main XS Weight=1
Downstream XS Weight=0
Number of DS XS's Weighted with US Boundary= 1
Upstream Boundary Weight= 1
Weight of XSs Associated with US Boundary= 0
Number of US XS's Weighted with DS Boundary= 1
Downstream Boundary Weight= 0.5
Weight of XSs Associated with DS Boundary= 0.5
Percentile Method= 0
Sediment Output Level= 3
Mass or Volume Output= 0
Output Increment Type= 1
Profile and TS Output Increment= 1
Transport Output Increment 1
XS Output Flag= 0
XS Output Increment= 10
Read HDF5 Sediment Hotstart= 0
Sediment Hotstart Type= 0
Write Gradation File= 0
Read Gradation Hotstart= 0
Write HDF5 File= 1
Write Binary Output= 1
Write DSS Sediment File= 0
DSS Sediment Output Type= 1
SV Curve= 0
Specific Gage Flag= 0
Subcell Erosion Methods= 0
Subcell Deposition Methods= 0
Advection Scheme= 1
Matrix Solver= 0
Implicit Weighting Factor= 1
Maximum Outer Loop Convergence Iterations= 5
Convergence Maximum Absolute= 0.001
Convergence RMSE= 0.0001
Grain Fractions Max Abs Error= 0.001
Max Subgrid Regions= 1
Max Subgrid Length Scale= 3.402823E+38
Initial Layer Thickness= 3.402823E+38
Min Layer Thickness= 3.402823E+38
Max Layer Thickness= 3.402823E+38
Number of Layers= 5

--- PECKSRNT3.f01 (steady flow) ---

Flow Title=Flows
Program Version=6.31
Number of Profiles= 1
Profile Names=01pct
River Rch & RM=PECKSRNT3,Main            ,4891
     344
Boundary for River Rch & Prof#=PECKSRNT3,Main            , 1
Up Type= 0
Dn Type= 3
Dn Slope=0.00434
DSS Import GetInterval= 0
DSS Import GetPeak= 0
DSS Import FillOption= 0

--- PECKSRNT3.g01 (geometry) ---

Geom Title=Geometry
Program Version=6.31

River Reach=PECKSRNT3       ,Main
Reach XY= 30
2203474.52319792756338.9034596682203493.66477039756254.490419954
2203538.64488678 756207.488725292203516.40752584756143.809009969
2203534.60173024756081.6454783232203501.94054511755769.544417098
2203471.12850021755618.0518631042203487.39041279755596.654609725
2203463.42548898755471.6946499352203419.77509207755384.393856123
2203376.98058531 755217.495279672203291.33600001755065.653000012
2203264.03600001754935.133000001        2203241.754638.839000002
     2203266.755754536.450000018     2203276.684754408.763000011
2203238.28100002753936.765000001     2203207.976753826.992000014
2203163.82099999753710.6379999972203114.42900005753647.253000006
2203110.70900004753617.7779999972203095.22800003753609.049999997
2202902.26800004753282.5080000162202742.64500001 752988.53200002
     2202621.398752820.0390000192202257.36900003752385.384000003
2202160.87400001      752252.9192202148.02499999752108.378000006
2202212.12600002751980.6060000212202227.09300002751921.026000008

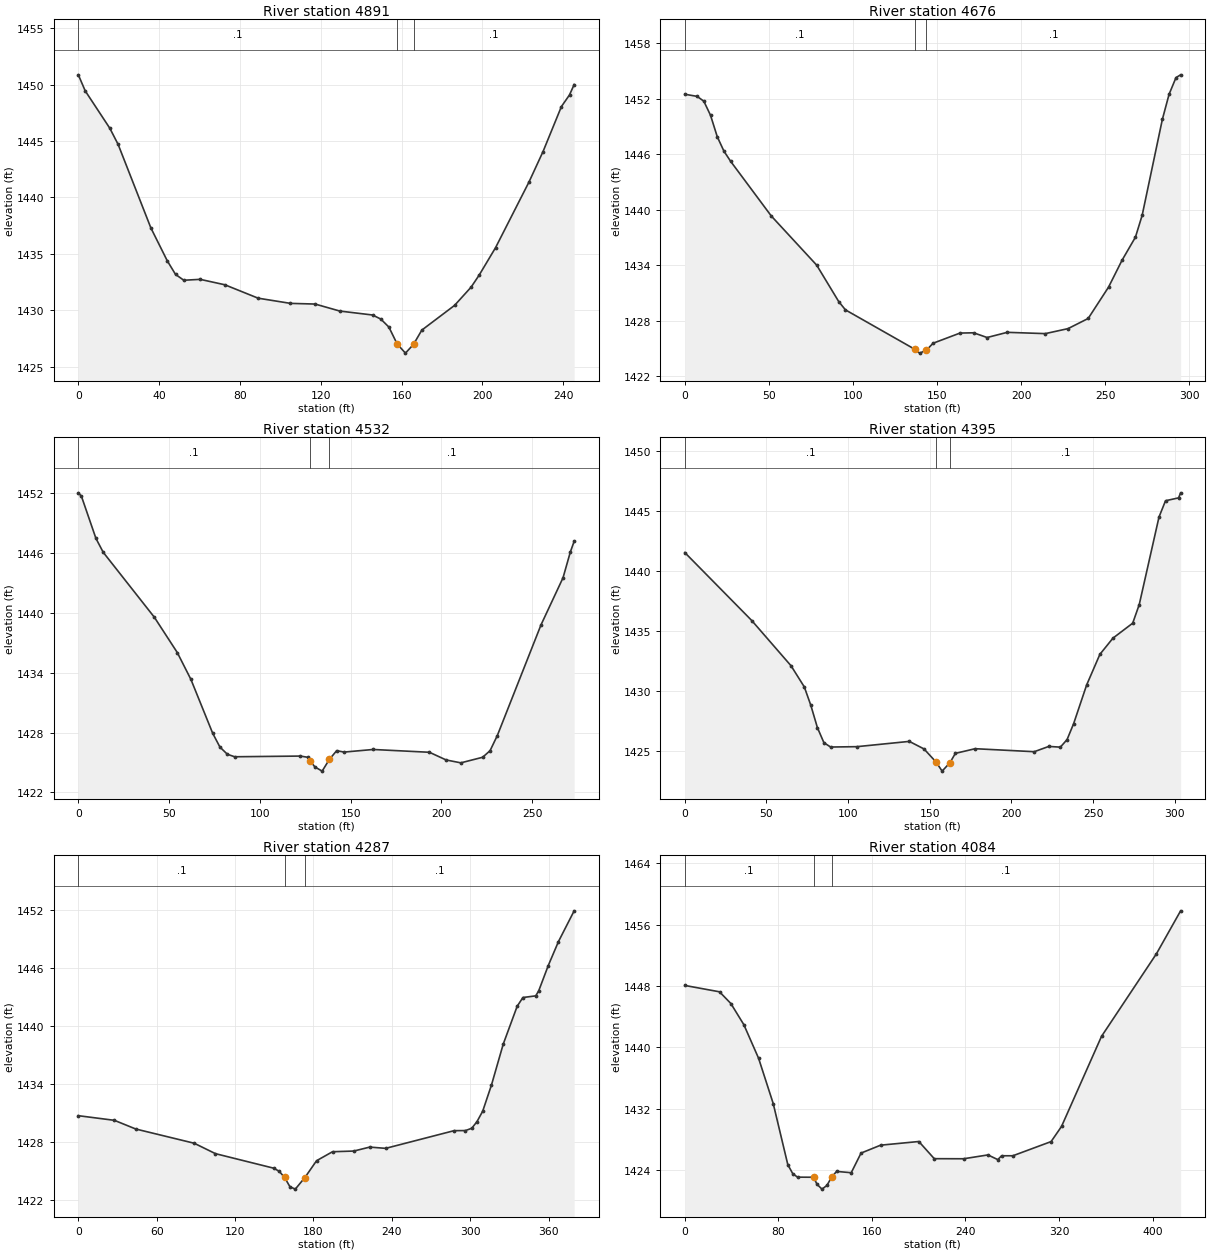
Type RM Length L Ch R = 1 ,4891    ,214.5,214.5,214.5
XS GIS Cut Line= 2
 2203635.5407271756360.4570564412203393.95981885756317.544658264
#Sta/Elev= 30
       0 1450.86     3.4 1449.44    15.6 1446.12    19.7 1444.69    35.9 1437.29
      44 1434.38    48.1 1433.17    52.2 1432.65    60.3 1432.73    72.5 1432.25
      89 1431.06     105  1430.6   117.2 1430.54   129.4 1429.92   145.6 1429.57
   149.7 1429.21   153.7  1428.5   157.8    1427   161.9 1426.19   165.9 1426.97
     170 1428.23   186.2 1430.42   194.4 1432.04   198.4 1433.11   206.5 1435.54
   223.1 1441.38     230 1444.06   239.1 1448.05   243.1 1449.08   245.4    1450
#Mann= 3 ,0,0
       0      .1       0   157.8    .045       0   165.9      .1       0
Bank Sta=157.8,165.9
XS Rating Curve= 0 ,0
Exp/Cntr(USF)=0,0
Exp/Cntr=0.3,0.1

Type RM Length L Ch R = 1 ,4676    ,144.1,144.1,144.1
XS GIS Cut Line= 2
2203655.41550352756136.669383334 2203361.3861086756157.330908383
#Sta/Elev= 30
       0 1452.48     7.3 1452.25    11.3 1451.73    15.3  1450.2    19.3 1447.88
    23.3 1446.31    27.3 1445.21    51.4 1439.31    78.4 1433.99    91.5 1430.05
    95.5 1429.15   136.6  1424.9   139.6 1424.47   143.6 1424.78   147.6 1425.54
   163.6 1426.64   171.7 1426.67   179.7 1426.16   191.7 1426.72   214.3 1426.58
   227.8 1427.12   239.8 1428.22   251.9 1431.61   259.9 1434.51   267.9 1437.02
   271.9 1439.39   283.9 1449.76   287.9 1452.48     292 1454.28294.7545 1454.58
#Mann= 3 ,-1,0
       0      .1       0   136.6    .045       0   143.6      .1       0
Bank Sta=136.6,143.6
XS Rating Curve= 0 ,0
Exp/Cntr(USF)=0,0
Exp/Cntr=0.3,0.1

Type RM Length L Ch R = 1 ,4532    ,136.4,136.4,136.4
XS GIS Cut Line= 2
2203653.82615544755995.2174041582203382.04763365756022.236321529
#Sta/Elev= 30
       0 1452.04     1.7  1451.7     9.7 1447.47    13.7 1446.08    41.9 1439.56
    54.5 1436.03      62 1433.34      74 1427.94      78 1426.55    82.1 1425.83
    86.1 1425.58   122.3 1425.65   126.3 1425.53   127.6  1425.2   130.3 1424.56
   134.3 1424.14   138.3 1425.32   142.3 1426.19   146.4 1426.05   162.4 1426.31
   193.4 1426.03   202.6 1425.26   210.7 1424.97   222.7 1425.53   226.8 1426.19
   230.8 1427.71   254.9 1438.82     267 1443.53     271  1446.1273.1183 1447.18
#Mann= 3 ,-1,0
       0      .1       0   127.6    .045       0   138.3      .1       0
Bank Sta=127.6,138.3
XS Rating Curve= 0 ,0
Exp/Cntr(USF)=0,0
Exp/Cntr=0.3,0.1

Type RM Length L Ch R = 1 ,4395    ,108.6,108.6,108.6
XS GIS Cut Line= 2
  2203664.951592755856.9441211442203362.97545668755888.731082756
#Sta/Elev= 30
       0 1441.52      41 1435.85    65.1 1432.07    73.2 1430.31    77.2 1428.77
    81.2 1426.92    85.2 1425.66    89.3  1425.3   105.4 1425.33   137.5 1425.77
   146.5 1425.14   153.8 1424.06   157.6 1423.29   162.4    1424   165.7 1424.77
   177.8 1425.16     214 1424.91   222.9 1425.35     230 1425.29   234.1 1425.92
   238.1 1427.24   246.1 1430.48   254.2 1433.03   262.2 1434.38   274.3 1435.63
   278.3 1437.18   290.4 1444.48   294.4 1445.84   302.4 1446.08303.6445  1446.5
#Mann= 3 ,-1,0
       0      .1       0   153.8    .045       0   162.4      .1       0
Bank Sta=153.8,162.4
XS Rating Curve= 0 ,0
Exp/Cntr(USF)=0,0
Exp/Cntr=0.3,0.1

Type RM Length L Ch R = 1 ,4287    ,202.5,202.5,202.5
XS GIS Cut Line= 3
2203663.36224392755736.153667016  2203369.332849755791.780849838
2203335.95653931755864.890861547
#Sta/Elev= 30
       0 1430.76    27.6 1430.28      44 1429.38    88.7 1427.91     105 1426.83
   149.8 1425.32   153.9 1424.99   157.9 1424.37     162 1423.41   166.1 1423.16
   173.4 1424.35   182.4  1426.1   194.6 1427.03   210.9  1427.1   223.1 1427.51
   235.3 1427.38   287.7 1429.21   296.4 1429.22   301.2 1429.46   305.2 1430.14
   309.6 1431.23   316.3 1433.93   325.3 1438.16     336 1442.09   340.4 1442.99
   350.2 1443.16   352.5 1443.69   359.8  1446.3   367.6 1448.78379.6134 1451.96
#Mann= 3 ,-1,0
       0      .1       0   157.9    .045       0   173.4      .1       0
Bank Sta=157.9,173.4
XS Rating Curve= 0 ,0
Exp/Cntr(USF)=0,0
Exp/Cntr=0.3,0.1

Type RM Length L Ch R = 1 ,4084    ,183.9,183.9,183.9
XS GIS Cut Line= 3
2203596.60962453755540.6638530982203297.81218537755629.667345613
2203192.91521205755589.933643598
#Sta/Elev= 30
       0 1448.08    29.7 1447.25    39.4 1445.72    50.5 1442.96    63.1 1438.58
    75.6 1432.68    88.1  1424.7    92.3 1423.54    96.4 1423.08   110.1 1423.07
   113.1 1422.14   117.3 1421.52   121.5    1422   125.7 1423.12   129.8 1423.83
   142.3 1423.66   150.7 1426.22   167.4 1427.25   200.1 1427.73   213.3 1425.49
   238.4 1425.48   259.2 1425.98   267.6 1425.37   270.9 1425.87   280.5 1425.87
   313.2 1427.72   322.1 1429.69   356.3 1441.44   403.3 1452.22423.9417 1457.81
#Mann= 3 ,-1,0
       0      .1       0   110.1    .045       0   125.7      .1       0
Bank Sta=110.1,125.7
XS Rating Curve= 0 ,0
Exp/Cntr(USF)=0,0
Exp/Cntr=0.3,0.1

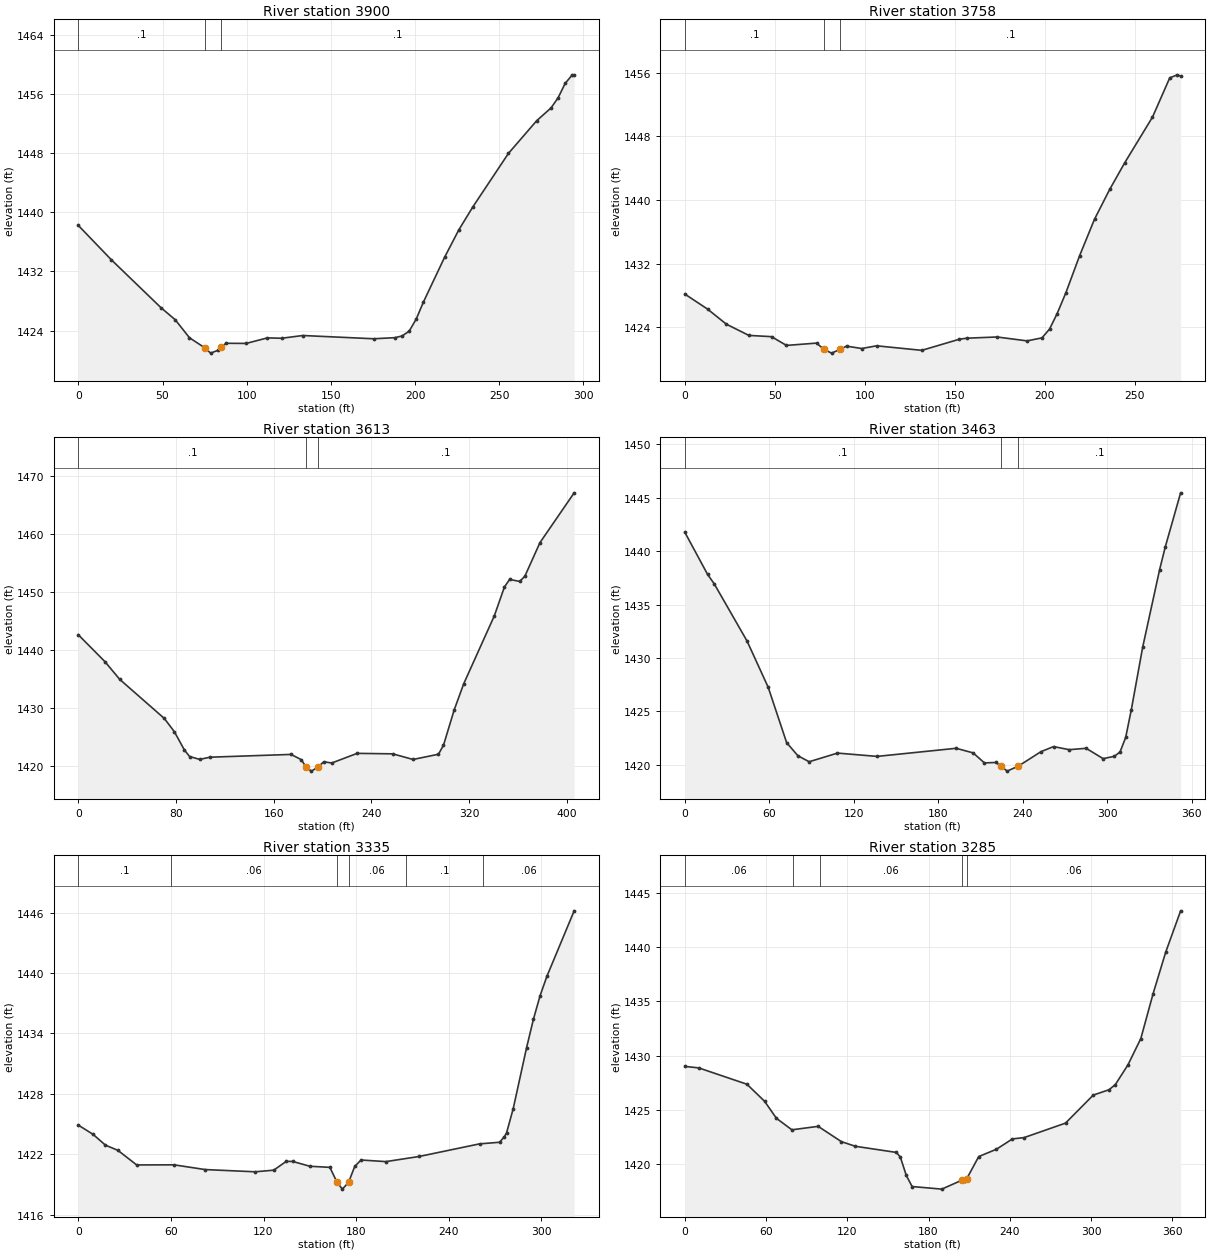
Type RM Length L Ch R = 1 ,3900    ,142.1,142.1,142.1
XS GIS Cut Line= 2
2203502.83808778755376.9610007932203223.11282559 755469.14318947
#Sta/Elev= 30
       0 1438.21    19.7 1433.55    49.1  1427.1    57.6 1425.46      66 1423.04
    75.1 1421.68    78.6 1420.96    82.8 1421.33    84.6 1421.76    87.8 1422.29
    99.7 1422.27   112.3 1423.02   120.7 1422.97   133.4 1423.34   175.5  1422.9
   188.1 1423.05   192.3 1423.28   196.5 1423.92   200.7 1425.56     205 1427.87
   217.6 1433.93     226 1437.61   234.4 1440.74   255.5 1447.95   272.3 1452.37
   280.8 1454.09     285 1455.46   289.2 1457.41   293.4 1458.55 294.523 1458.56
#Mann= 3 ,-1,0
       0      .1       0    75.1    .045       0    84.6      .1       0
Bank Sta=75.1,84.6
XS Rating Curve= 0 ,0
Exp/Cntr(USF)=0,0
Exp/Cntr=0.3,0.1

Type RM Length L Ch R = 1 ,3758    ,423.5,145.6,423.5
XS GIS Cut Line= 2
2203466.28308192 755243.455762022203202.45130054755322.923166052
#Sta/Elev= 30
       0 1428.18    12.7 1426.28    23.1 1424.39    35.6 1422.98    48.2 1422.82
    56.5 1421.72    73.2 1422.01    77.4 1421.21    81.6 1420.75    86.5 1421.25
    89.9 1421.63    98.3 1421.33   106.6 1421.67   131.7  1421.1   152.6  1422.5
   156.8 1422.63   173.5 1422.78   190.2 1422.29   198.5 1422.67   202.7 1423.78
   206.9 1425.71   211.8 1428.36   219.4    1433   227.7  1437.6   236.1 1441.33
   244.5  1444.7   259.9 1450.43   269.5 1455.37   273.7 1455.75  275.54 1455.58
#Mann= 3 ,-1,0
       0      .1       0    77.4    .045       0    86.5      .1       0
Bank Sta=77.4,86.5
XS Rating Curve= 0 ,0
Exp/Cntr(USF)=0,0
Exp/Cntr=0.3,0.1

Type RM Length L Ch R = 1 ,3613    ,149.7,149.7,149.7
XS GIS Cut Line= 3
 2203521.6637982755092.9072914162203445.44506408 755105.51718844
2203129.32166267755195.576244446
#Sta/Elev= 30
       0 1442.56    21.8 1437.93    33.9 1434.88    70.4 1428.15    78.6 1425.87
    86.9  1422.7    91.1 1421.59    99.4 1421.09   107.7 1421.47   174.2 1421.95
   182.6 1421.04   186.7  1419.7   190.9 1419.07   195.9 1419.73     201 1420.68
   207.5 1420.47   228.3 1422.13   257.4 1422.05   274.1 1421.08   294.9 1421.98
     299 1423.53   307.8 1429.64   315.6 1434.14   340.6 1445.81   348.9 1450.79
   353.1 1452.09   361.4 1451.76   365.6 1452.64     378 1458.44     406 1467.02
#Mann= 3 ,-1,0
       0      .1       0   186.7    .045       0   195.9      .1       0
Bank Sta=186.7,195.9
XS Rating Curve= 0 ,0
Exp/Cntr=0.3,0.1

Type RM Length L Ch R = 1 ,3463    ,128.6,128.2,127.6
XS GIS Cut Line= 3
2203504.34901035754987.5605228972203440.07143466754990.433567454
2203153.27322835755013.228322773
#Sta/Elev= 30
       0 1441.78    16.2 1437.82    20.9 1436.94    44.2 1431.58    59.2 1427.25
    72.3 1422.06    80.3 1420.83    88.3 1420.27   108.4 1421.08   136.5 1420.77
   192.6 1421.53   204.7  1421.1   212.7 1420.16   220.7  1420.2   224.7 1419.86
   228.8 1419.39   236.8 1419.86   252.8 1421.21   261.8 1421.69   272.9  1421.4
   284.9 1421.53     297 1420.56     305 1420.78     309 1421.19     313 1422.55
     317 1425.15   325.1 1431.03   337.1 1438.28   341.1  1440.4     352 1445.47
#Mann= 3 ,-1,0
       0      .1       0   224.7    .045       0   236.8      .1       0
Bank Sta=224.7,236.8
XS Rating Curve= 0 ,0
Exp/Cntr=0.3,0.1

Type RM Length L Ch R = 1 ,3335    ,51.5,49.6,47.6
XS GIS Cut Line= 3
2203433.57398055754853.1586002512203233.36189562754881.313424695
2203123.87091167754928.238132101
#Sta/Elev= 30
       0 1424.91     9.5    1424    17.6 1422.92    25.6 1422.41    37.8 1420.96
      62 1420.97    82.2  1420.5   114.6 1420.28   126.6 1420.44   134.7 1421.31
   138.8 1421.31     150 1420.83     163 1420.72   167.7 1419.22   171.1 1418.56
   175.1 1419.23   179.1 1420.81   183.2 1421.45   199.3 1421.29   220.9  1421.8
     260 1423.05     273 1423.21   276.1 1423.77   277.5 1424.14   281.8 1426.54
   290.5 1432.61   294.9 1435.41   299.2 1437.74   303.6 1439.66   321.3 1446.17
#Mann= 6 ,-1,0
       0      .1       0      60     .06       0   167.7    .045       0
   175.1     .06       0  212.18      .1       0  262.18     .06       0
Bank Sta=167.7,175.1
XS Rating Curve= 0 ,0
Exp/Cntr(USF)=0,0
Exp/Cntr=0.3,0.1

Type RM Length L Ch R = 1 ,3285    ,76.1,74.1,73.3
XS GIS Cut Line= 3
2203450.25832096754745.7531588542203185.39441694754860.457999181
2203118.65705529754900.083307657
#Sta/Elev= 30
       0    1429    10.3 1428.86    45.9 1427.35    58.9 1425.78    67.7  1424.2
    79.1 1423.14    98.5 1423.46   115.6 1422.05   125.9 1421.62   156.3 1421.05
   159.2 1420.62   163.6 1418.92   167.9  1417.9   189.8 1417.66   204.61418.483
   207.1 1418.37   208.31418.635   217.1 1420.67   230.1 1421.34     242  1422.3
   250.6 1422.42   281.2 1423.76   301.7 1426.35   313.3 1426.84     318 1427.32
   327.3 1429.14   336.8 1431.57   345.9 1435.73   355.2 1439.56   366.2 1443.37
#Mann= 5 ,-1,0
       0     .06       0      80      .1       0     100     .06       0
   204.6    .045       0   208.3     .06       0
Bank Sta=204.6,208.3
XS Rating Curve= 0 ,0
Exp/Cntr(USF)=0,0
Exp/Cntr=0.3,0.1

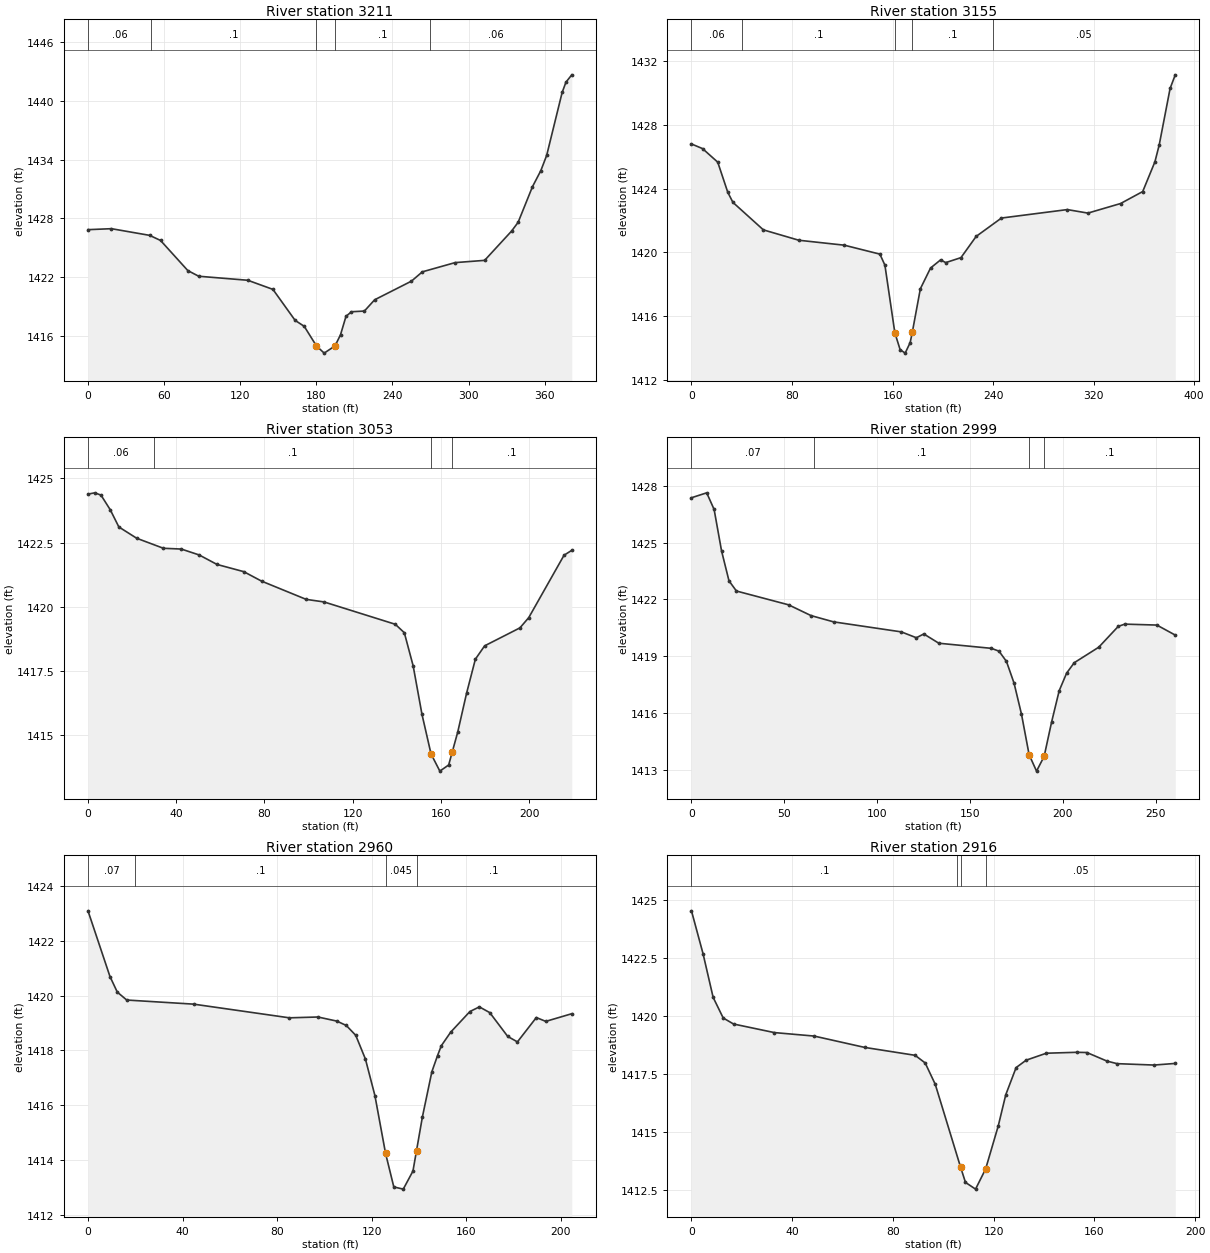
Type RM Length L Ch R = 1 ,3211    ,51.7,55.7,58.2
XS GIS Cut Line= 3
2203429.40289545754685.2724248632203138.46970953 754799.97726519
2203079.03174681754834.388717288
#Sta/Elev= 30
       0 1426.86    18.5 1426.96    48.6 1426.28    57.2 1425.76    78.7 1422.69
    87.3 1422.11     126  1421.7   145.8 1420.77   163.3 1417.61   170.5    1417
   180.11415.006   186.2 1414.27   194.8 1415.01   199.1 1416.15   203.4 1418.02
   207.7 1418.49   217.9 1418.56     226 1419.71     255 1421.61   263.6 1422.56
   289.4  1423.5   312.7 1423.73   333.9 1426.71   339.1 1427.61   350.4 1431.24
     357 1432.88   361.6 1434.43   373.8 1440.85   376.8  1441.9   381.4 1442.65
#Mann= 6 ,-1,0
       0     .06       0      50      .1       0   180.1    .045       0
   194.8      .1       0     270     .06       0  372.73     .05       0
Bank Sta=180.1,194.8
XS Rating Curve= 0 ,0
Exp/Cntr(USF)=0,0
Exp/Cntr=0.3,0.1

Type RM Length L Ch R = 1 ,3155    ,99.4,102.3,104.7
XS GIS Cut Line= 3
2203416.88964014754679.0157972092203107.18657126 754717.59833441
2203040.44920961754746.795930129
#Sta/Elev= 30
       0 1426.79     8.8  1426.5    20.9 1425.65    28.9 1423.76      33 1423.13
    57.2 1421.41    85.4 1420.76   121.6 1420.45   149.9 1419.89   153.9  1419.2
   161.81414.965     166 1413.91     170 1413.69     174 1414.35  175.77 1415.03
   182.1 1417.72   190.2 1419.02   198.2 1419.53   202.3 1419.36   214.4 1419.67
   226.5    1421   246.6 1422.15     299 1422.68   315.4 1422.46   341.4 1423.06
     359 1423.81   368.7 1425.67   372.1 1426.72   380.8 1430.27   384.9 1431.12
#Mann= 5 ,-1,0
       0     .06       0      40      .1       0   161.8    .045       0
  175.77      .1       0     240     .05       0
Bank Sta=161.8,175.77
XS Rating Curve= 0 ,0
Exp/Cntr(USF)=0,0
Exp/Cntr=0.3,0.1

Type RM Length L Ch R = 1 ,3053    ,53.7,54.3,54.4
XS GIS Cut Line= 4
2203409.98174288754622.8834149022203288.96268835754604.571321125
2203222.87991516754595.8133632322203192.62515153754595.813363231
#Sta/Elev= 30
       0 1424.39     3.1 1424.44     5.9 1424.35    10.1 1423.78      14 1423.11
    22.1 1422.67    34.2 1422.28    42.3 1422.25    50.4 1422.02    58.5 1421.65
    70.6 1421.37    78.7    1421    98.9 1420.29     107 1420.19   139.3 1419.32
   143.4 1418.99   147.4  1417.7   151.4 1415.81   155.5 1414.27   159.5  1413.6
   163.5 1413.84  165.171414.361   167.6 1415.12   171.6 1416.63   175.6 1417.96
   179.8 1418.48   195.8 1419.18   199.8 1419.58   215.8 1422.01   219.3  1422.2
#Mann= 4 ,-1,0
       0     .06       0      30      .1       0   155.5    .045       0
  165.17      .1       0
Bank Sta=155.5,165.17
XS Rating Curve= 0 ,0
Exp/Cntr(USF)=0,0
Exp/Cntr=0.3,0.1

Type RM Length L Ch R = 1 ,2999    ,39.4,38.8,38.2
XS GIS Cut Line= 3
2203448.34103863754570.9458570592203392.25186104754567.394981535
2203190.42836688754535.918430689
#Sta/Elev= 30
       0 1427.37     8.2 1427.63    12.2 1426.75    16.2 1424.56    20.2 1422.98
    24.2 1422.44    52.3 1421.71    64.4 1421.14    76.5 1420.81     113 1420.28
   121.1 1419.97   125.1 1420.17   133.2 1419.68   161.5 1419.41   165.6 1419.26
   169.6 1418.72   173.7 1417.57   177.7 1415.93   181.8 1413.79   185.8 1412.92
   189.9  1413.7   193.9 1415.51     198 1417.17     202  1418.1   206.1 1418.65
   219.3 1419.47   229.8 1420.57   233.3 1420.69   250.6 1420.64   260.5 1420.11
#Mann= 4 ,-1,0
       0     .07       0    66.2      .1       0   181.8    .045       0
   189.9      .1       0
Bank Sta=181.8,189.9
XS Rating Curve= 0 ,0
Exp/Cntr=0.3,0.1

Type RM Length L Ch R = 1 ,2960    ,45.5,44,43.1
XS GIS Cut Line= 3
2203400.39801964754498.7739451982203307.53181886754512.703875316
2203197.25320542754502.256427728
#Sta/Elev= 30
       0  1423.1     9.3  1420.7    12.4 1420.13    16.4 1419.84    44.7 1419.69
    85.2 1419.19    97.3 1419.22   105.3 1419.07   109.3 1418.91   113.3 1418.55
   117.4 1417.68   121.4 1416.35   125.9 1414.24   129.4 1413.01   133.4 1412.93
   137.5 1413.59     1391414.333   141.5 1415.57   145.5 1417.22   147.9 1417.81
   149.5 1418.17   153.5 1418.67   161.6 1419.42   165.6 1419.59     170 1419.38
   177.6 1418.51   181.7 1418.31   189.7  1419.2   193.7 1419.06   204.7 1419.34
#Mann= 4 ,-1,0
       0     .07       0      20      .1       0   125.9    .045       0
     139      .1       0
Bank Sta=125.9,139
XS Rating Curve= 0 ,0
Exp/Cntr(USF)=0,0
Exp/Cntr=0.3,0.1

Type RM Length L Ch R = 1 ,2916    ,37.9,37.9,37.7
XS GIS Cut Line= 4
2203388.78974454754458.7253961092203303.46892257754464.529533658
2203249.49044336754466.8511886782203197.25320542754472.655326227
#Sta/Elev= 26
       0 1424.53     4.6 1422.68     8.6  1420.8    12.6 1419.91    16.7 1419.65
    32.9 1419.28    48.7 1419.13    68.8 1418.64    88.8  1418.3    92.8 1417.97
    96.8 1417.05  106.831413.485   108.8 1412.82   112.8 1412.53   116.8  1413.4
   121.8 1415.25   124.8  1416.6   128.9 1417.77   132.9 1418.09   140.9 1418.39
   152.9 1418.43     157 1418.42     165 1418.05     169 1417.94   183.7 1417.88
   192.1 1417.95
#Mann= 4 ,-1,0
       0      .1       0  105.52     .05       0  106.83    .045       0
   116.8     .05       0
Bank Sta=106.83,116.8
XS Rating Curve= 0 ,0
Exp/Cntr(USF)=0,0
Exp/Cntr=0.3,0.1

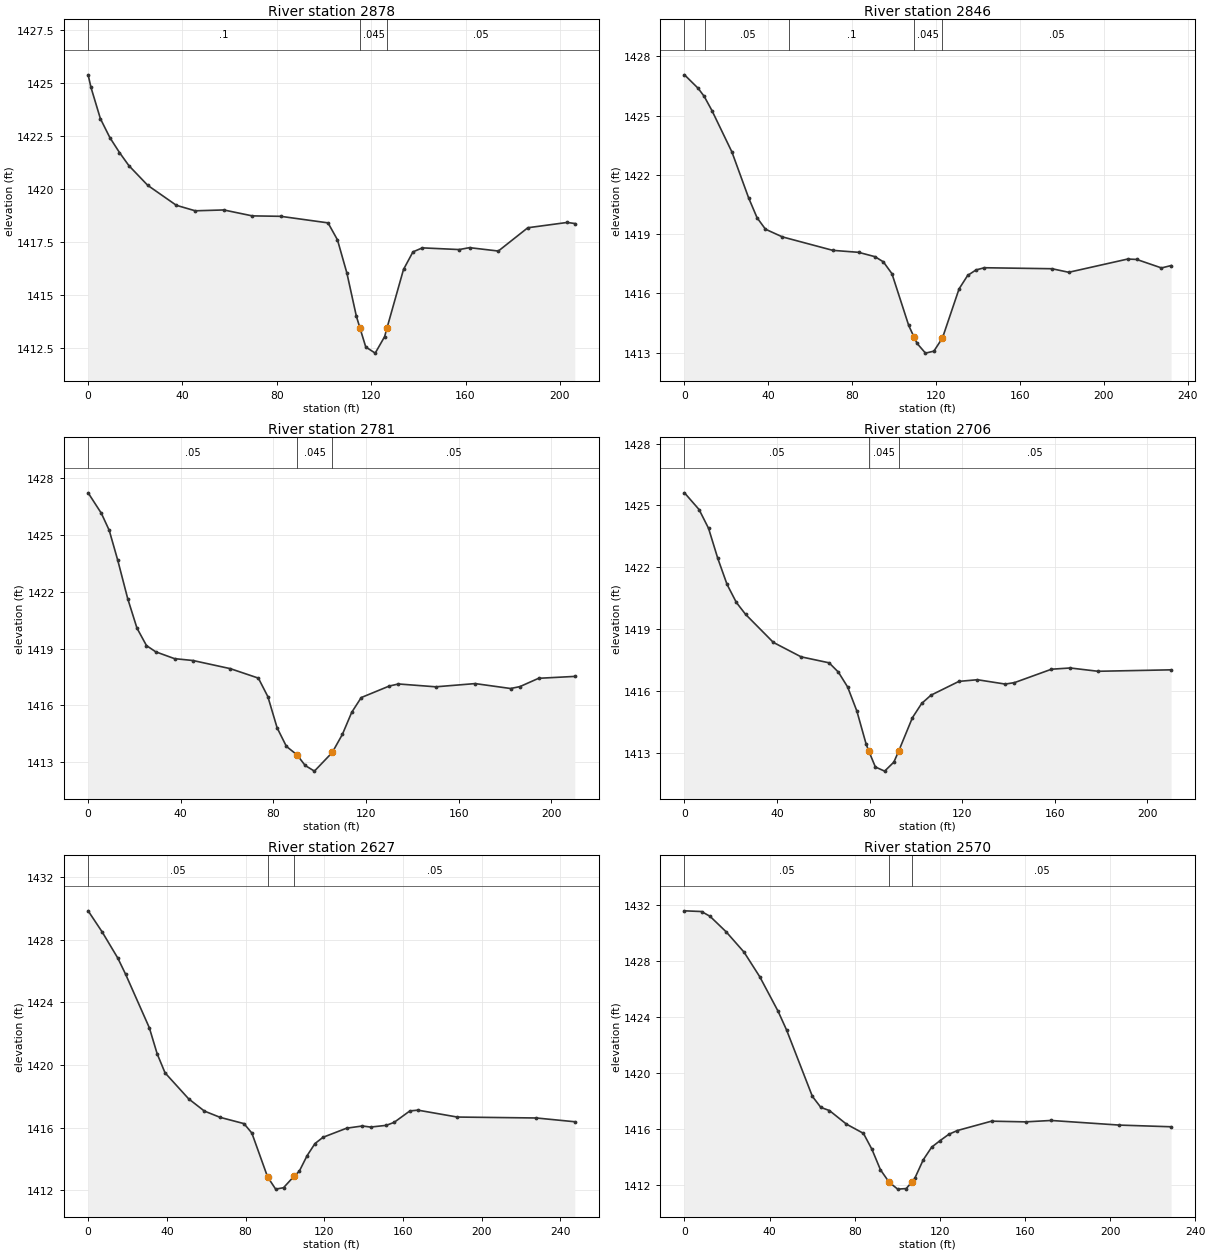
Type RM Length L Ch R = 1 ,2878    ,32.5,32.1,31.6
XS GIS Cut Line= 4
2203397.36023785754417.515182398 2203317.4372638754425.977614945
2203228.37277311 754430.156593982203193.12968366754440.710721457
#Sta/Elev= 30
       0 1425.38     1.2 1424.79     5.2 1423.31     9.2 1422.42    13.3 1421.71
    17.3 1421.09    25.3 1420.16    37.4 1419.22    45.4 1418.96    57.5    1419
    69.6 1418.72    81.6  1418.7   101.7 1418.39   105.7 1417.59   109.7 1416.02
   113.7 1413.99   115.2 1413.44   117.7 1412.53   121.7 1412.24   125.7 1413.02
  126.711413.431   133.7 1416.19   137.7 1417.02   141.7 1417.21   157.3 1417.13
   161.7 1417.22   173.9 1417.06   186.4 1418.16   203.1 1418.41   206.3 1418.36
#Mann= 3 ,-1,0
       0      .1       0   115.2    .045       0  126.71     .05       0
Bank Sta=115.2,126.71
XS Rating Curve= 0 ,0
Exp/Cntr(USF)=0,0
Exp/Cntr=0.3,0.1

Type RM Length L Ch R = 1 ,2846    ,65.1,64.8,64.2
XS GIS Cut Line= 2
2203390.63596059754385.4547792162203159.61738899754406.358755733
#Sta/Elev= 30
       0 1427.06     6.5 1426.38     9.4 1425.97    13.1 1425.25    22.6 1423.16
    30.6 1420.83    34.6 1419.83    38.6 1419.25    46.7 1418.86    70.7 1418.18
      83 1418.08    90.8 1417.86    94.8  1417.6    98.9    1417   106.9 1414.38
  109.451413.788   110.9 1413.47   114.9 1412.98   118.9 1413.08     123 1413.75
   130.9 1416.23     135 1416.91     139 1417.19     143  1417.3   175.2 1417.25
   183.2 1417.07   211.3 1417.74   215.6 1417.72   227.4 1417.29     232 1417.41
#Mann= 5 ,-1,0
       0      .1       0      10     .05       0      50      .1       0
  109.45    .045       0     123     .05       0
Bank Sta=109.45,123
XS Rating Curve= 0 ,0
Exp/Cntr=0.3,0.1

Type RM Length L Ch R = 1 ,2781    ,74.5,75.4,76.1
XS GIS Cut Line= 2
2203365.15721592754319.8587636052203156.63820026 754345.65493049
#Sta/Elev= 30
       0 1427.24     5.7 1426.16     9.1 1425.26    12.8 1423.67    17.1 1421.64
    21.1 1420.08    25.2 1419.16    29.2 1418.83    37.3 1418.47    45.3 1418.37
    61.4 1417.94    73.5 1417.44    77.6 1416.46    81.6 1414.81    85.6 1413.83
    90.2 1413.38    93.7 1412.82    97.7 1412.52   105.41413.507   109.8 1414.47
   113.8 1415.63   117.9 1416.41     130 1417.02     134 1417.13   150.1 1416.98
   167.1 1417.15   182.4 1416.89   186.4 1416.99   194.5 1417.43   210.1 1417.53
#Mann= 3 ,-1,0
       0     .05       0    90.2    .045       0   105.4     .05       0
Bank Sta=90.2,105.4
XS Rating Curve= 0 ,0
Exp/Cntr(USF)=0,0
Exp/Cntr=0.3,0.1

Type RM Length L Ch R = 1 ,2706    ,79.5,79.2,78.9
XS GIS Cut Line= 2
2203350.50487096754251.4153031092203140.64740553754264.759768841
#Sta/Elev= 30
       0 1425.61     6.3  1424.8    10.4 1423.89    14.4 1422.43    18.4 1421.17
    22.4  1420.3    26.4 1419.72    38.4 1418.36    50.4 1417.66    62.5 1417.37
    66.5 1416.92    70.5  1416.2    74.5 1415.03    78.5 1413.43    79.61413.103
    82.5 1412.32    86.5 1412.12    90.5 1412.56   92.56 1413.09    98.5 1414.71
   102.5  1415.4   106.5  1415.8   118.6 1416.47   126.6 1416.55   138.6 1416.34
   142.6 1416.41   158.6 1417.06   166.7 1417.12   178.7 1416.96   210.3 1417.03
#Mann= 3 ,-1,0
       0     .05       0    79.6    .045       0   92.56     .05       0
Bank Sta=79.6,92.56
XS Rating Curve= 0 ,0
Exp/Cntr=0.3,0.1

Type RM Length L Ch R = 1 ,2627    ,56,56.3,56.3
XS GIS Cut Line= 3
2203355.23134828754175.098266318 2203305.0721349754173.665145936
2203108.73464249754191.579150717
#Sta/Elev= 30
       0 1429.84     7.1  1428.5    15.1 1426.82    19.1 1425.78    31.1 1422.38
    35.1 1420.71    39.1  1419.5    51.1 1417.84    59.1 1417.06    67.1 1416.66
    79.2 1416.26    83.2 1415.66    91.2 1412.86    95.3 1412.08    99.3 1412.17
   104.7 1412.91   107.3 1413.22   111.3 1414.22   115.3 1414.99   119.4 1415.39
   131.4 1415.97   139.4 1416.11   143.5 1416.04   151.5 1416.15   155.5 1416.34
   163.5 1417.07   167.6 1417.12   187.6 1416.68   227.8 1416.62   247.3 1416.38
#Mann= 3 ,-1,0
       0     .05       0    91.2    .045       0   104.7     .05       0
Bank Sta=91.2,104.7
XS Rating Curve= 0 ,0
Exp/Cntr(USF)=0,0
Exp/Cntr=0.3,0.1

Type RM Length L Ch R = 1 ,2570    ,140.5,140.1,138.5
XS GIS Cut Line= 2
2203352.10742161754115.4320292762203123.90885658754131.027414892
#Sta/Elev= 30
       0  1431.6       8 1431.55      12 1431.21    19.6  1430.1      28 1428.65
    35.4 1426.89      44 1424.43      48 1423.09    60.1 1418.36    64.1 1417.57
    68.1 1417.35    76.1 1416.38    84.1 1415.72    88.1 1414.58    92.1 1413.12
    96.2 1412.23   100.2 1411.74   104.2 1411.78   106.7 1412.22   108.2  1412.5
   112.2 1413.83   116.2 1414.74   120.2 1415.21   124.2 1415.65   128.2 1415.92
   144.3 1416.59   160.3 1416.54   172.3 1416.64   204.4 1416.31   228.7 1416.19
#Mann= 3 ,-1,0
       0     .05       0    96.2    .045       0   106.7     .05       0
Bank Sta=96.2,106.7
XS Rating Curve= 0 ,0
Exp/Cntr=0.3,0.1

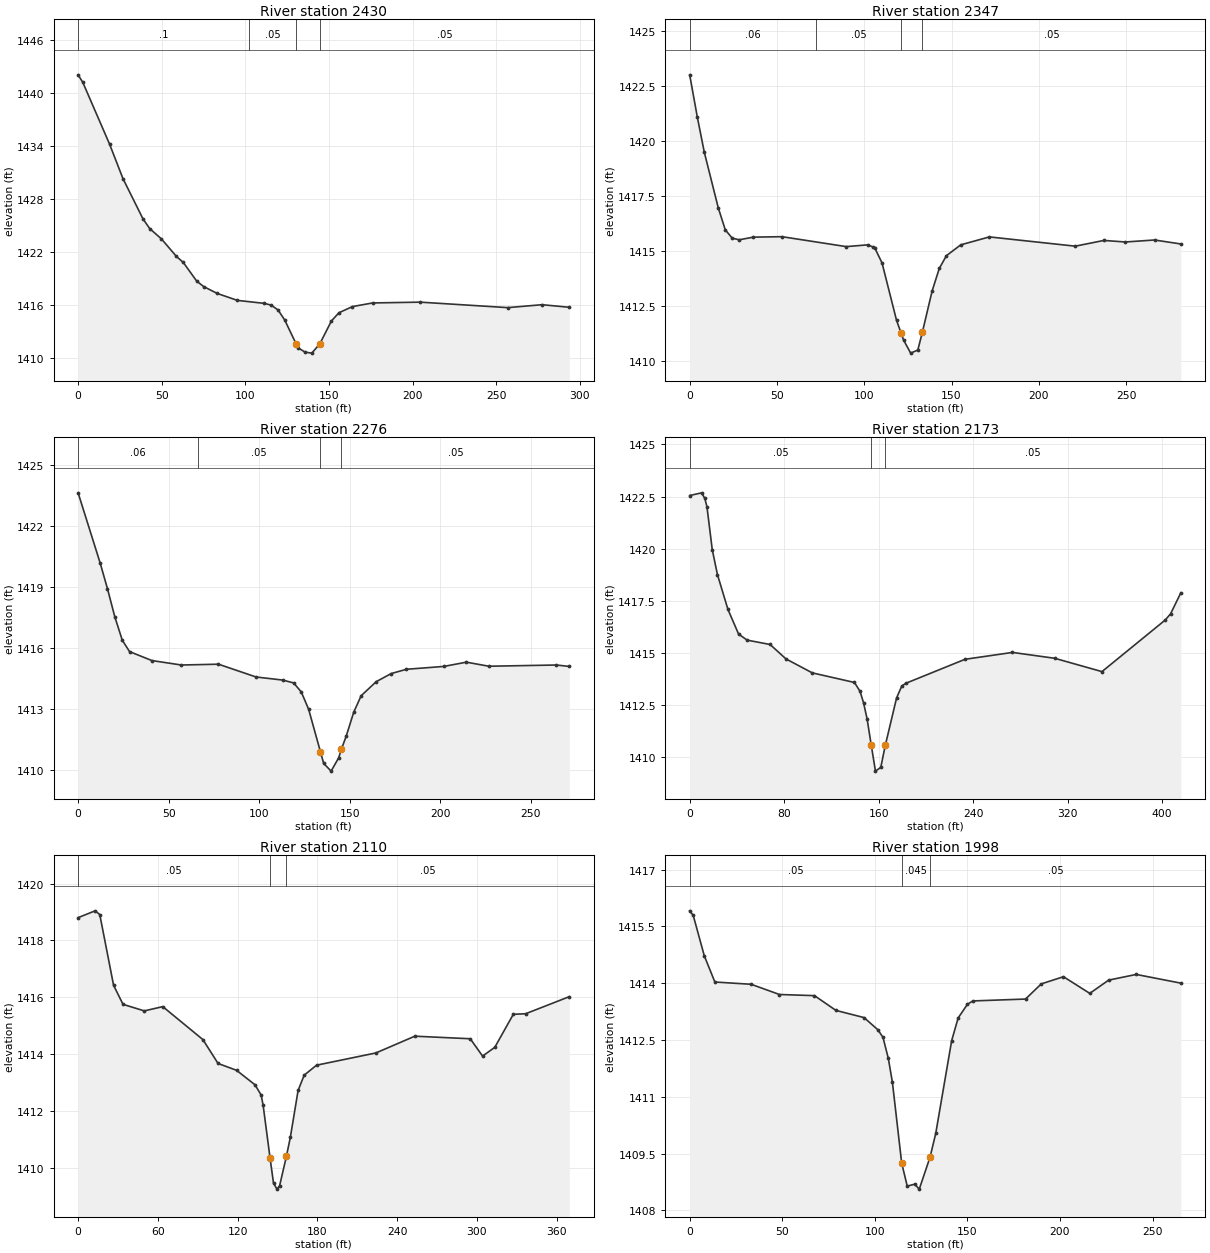
Type RM Length L Ch R = 1 ,2430    ,83.6,83.3,82.1
XS GIS Cut Line= 3
2203379.01877943753971.5773409232203316.79651052753972.310078657
2203088.00033986754006.950138181
#Sta/Elev= 30
       0 1442.01     2.8 1441.16    18.8 1434.17    26.8 1430.27    38.8  1425.7
    42.8 1424.61    49.8 1423.44    58.8 1421.45    62.9 1420.77    70.9 1418.66
      75 1418.05    83.1 1417.27    95.2 1416.48   111.4 1416.14   115.4 1415.94
   119.5  1415.4   123.5 1414.26   130.3 1411.57   131.6  1411.1   135.7 1410.62
   139.7 1410.51  144.471411.556   151.4 1414.14   155.9 1415.08     164 1415.78
   176.1 1416.19   204.5 1416.28   256.8 1415.66   277.3 1415.99   293.6  1415.7
#Mann= 4 ,-1,0
       0      .1       0  102.23     .05       0   130.3    .045       0
  144.47     .05       0
Bank Sta=130.3,144.47
XS Rating Curve= 0 ,0
Exp/Cntr=0.3,0.1

Type RM Length L Ch R = 1 ,2347    ,72.1,71.5,71
XS GIS Cut Line= 3
2203352.53605984753883.214628728 2203320.4320126 753882.36978538
2203077.11712819753936.439759693
#Sta/Elev= 30
       0 1422.99     4.4 1421.06     8.4 1419.47    16.4 1416.95    20.4 1415.96
    24.4 1415.58    28.4 1415.51    36.5 1415.63    52.9 1415.65    89.7  1415.2
     102 1415.28   105.1 1415.18   106.1 1415.13   110.2 1414.46   118.5 1411.86
   121.11411.281   122.5 1410.97   126.6 1410.37   130.7 1410.51  133.291411.312
   138.9 1413.19     143 1414.21   147.1 1414.79   155.3 1415.28   171.7 1415.64
   220.9 1415.22   237.3 1415.48   249.6 1415.41   266.3  1415.5   281.4 1415.32
#Mann= 4 ,-1,0
       0     .06       0   72.12     .05       0   121.1    .045       0
  133.29     .05       0
Bank Sta=121.1,133.29
XS Rating Curve= 0 ,0
Exp/Cntr(USF)=0,0
Exp/Cntr=0.3,0.1

Type RM Length L Ch R = 1 ,2276    ,104.3,102.9,100
XS GIS Cut Line= 3
2203344.08762636753802.1096672592203279.03468851753814.782317489
2203081.34134493753868.852291802
#Sta/Elev= 30
       0 1423.62    12.1 1420.19    16.2 1418.91    20.3 1417.51    24.4 1416.37
    28.4 1415.81    40.7 1415.37      57 1415.15    77.5 1415.19    98.3 1414.56
   112.9 1414.41     119 1414.27   123.2 1413.83   127.3 1412.97   133.81410.884
   135.6 1410.31   139.7 1409.93   143.9 1410.59   145.4 1411.01     148 1411.64
   152.2 1412.83   156.3 1413.64   164.6 1414.33   172.9 1414.73   181.3 1414.94
   201.9 1415.08   214.4 1415.29   226.8 1415.09   264.1 1415.15   271.2 1415.08
#Mann= 4 ,-1,0
       0     .06       0   66.28     .05       0   133.8    .045       0
   145.4     .05       0
Bank Sta=133.8,145.4
XS Rating Curve= 0 ,0
Exp/Cntr(USF)=0,0
Exp/Cntr=0.3,0.1

Type RM Length L Ch R = 1 ,2173    ,62.7,62.1,61.2
XS GIS Cut Line= 2
2203317.27795002753669.1850404142202944.29650485753853.099336916
#Sta/Elev= 30
       0 1422.55    10.1 1422.68    12.8 1422.41    14.6 1422.02    19.1 1419.96
    23.5 1418.76    32.4 1417.09    41.4 1415.91    48.6 1415.62    68.1 1415.41
    81.5 1414.72   103.8 1414.05   139.5 1413.59   144.2 1413.17   147.2 1412.62
   150.2 1411.85   153.7  1410.6   157.3 1409.34   161.8 1409.52  165.621410.573
   175.2 1412.85   179.6 1413.42     183 1413.55   233.1  1414.7   273.3 1415.03
     309 1414.75   349.1 1414.11   402.6 1416.58   407.2 1416.88   415.9 1417.89
#Mann= 3 ,-1,0
       0     .05       0   153.7    .045       0  165.62     .05       0
Bank Sta=153.7,165.62
XS Rating Curve= 0 ,0
Exp/Cntr=0.3,0.1

Type RM Length L Ch R = 1 ,2110    ,115.8,112,105.4
XS GIS Cut Line= 2
2203275.23945739753609.9702113082202955.81678638753795.667363849
#Sta/Elev= 30
       0  1418.8    12.8 1419.04    16.3 1418.91    26.7 1416.42    33.8 1415.75
    49.8 1415.52    63.7 1415.67    93.9 1414.51   105.3 1413.67   119.2 1413.43
   133.1 1412.92   137.7 1412.56   139.2  1412.2  144.361410.362     147 1409.46
   149.6 1409.25   151.6 1409.37   156.7  1410.4   159.7 1411.08   165.5 1412.72
   170.1 1413.26   179.4 1413.61     224 1414.04   253.3 1414.63     295 1414.54
   304.3 1413.93   313.5 1414.24   327.4  1415.4   336.7 1415.42   369.5 1416.02
#Mann= 3 ,-1,0
       0     .05       0  144.36    .045       0   156.7     .05       0
Bank Sta=144.36,156.7
XS Rating Curve= 0 ,0
Exp/Cntr=0.3,0.1

Type RM Length L Ch R = 1 ,1998    ,18,19.5,20.5
XS GIS Cut Line= 2
2203168.57795316753498.9658007922203005.09738735753707.888422185
#Sta/Elev= 30
       0 1415.91     1.9 1415.79     7.9 1414.72    13.6 1414.03    33.2 1413.97
    48.5  1413.7    67.4 1413.67      79 1413.28    94.2 1413.09   101.6 1412.77
   104.4 1412.57   107.3 1412.01   109.5 1411.38   114.5 1409.25   117.5 1408.64
   121.5 1408.69     124 1408.56   129.8  1409.4   132.9 1410.03   141.5 1412.48
     145 1413.08     150 1413.44   152.9 1413.53   181.4 1413.58   189.9 1413.98
   201.9 1414.17   216.1 1413.73   226.3 1414.08   241.2 1414.23   265.3    1414
#Mann= 3 ,-1,0
       0     .05       0   114.5    .045       0   129.8     .05       0
Bank Sta=114.5,129.8
XS Rating Curve= 0 ,0
Exp/Cntr(USF)=0,0
Exp/Cntr=0.3,0.1