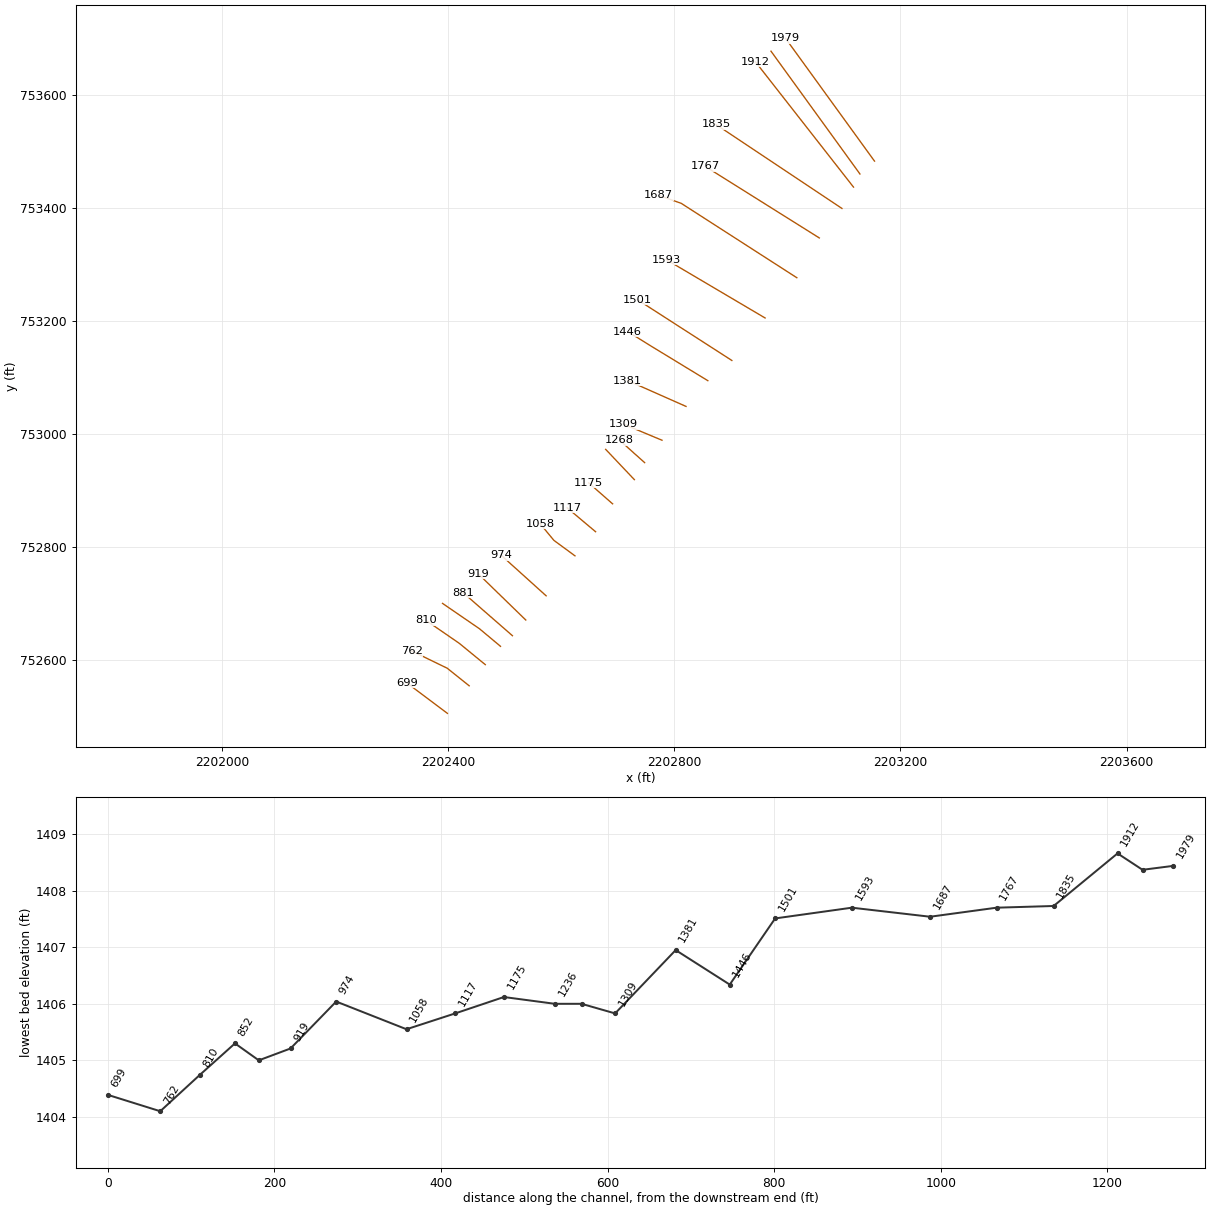
HEC-RAS study PECKSRNT3.prj: PECKSRNT3

--- PECKSRNT3.g01 (geometry) --- (continued)

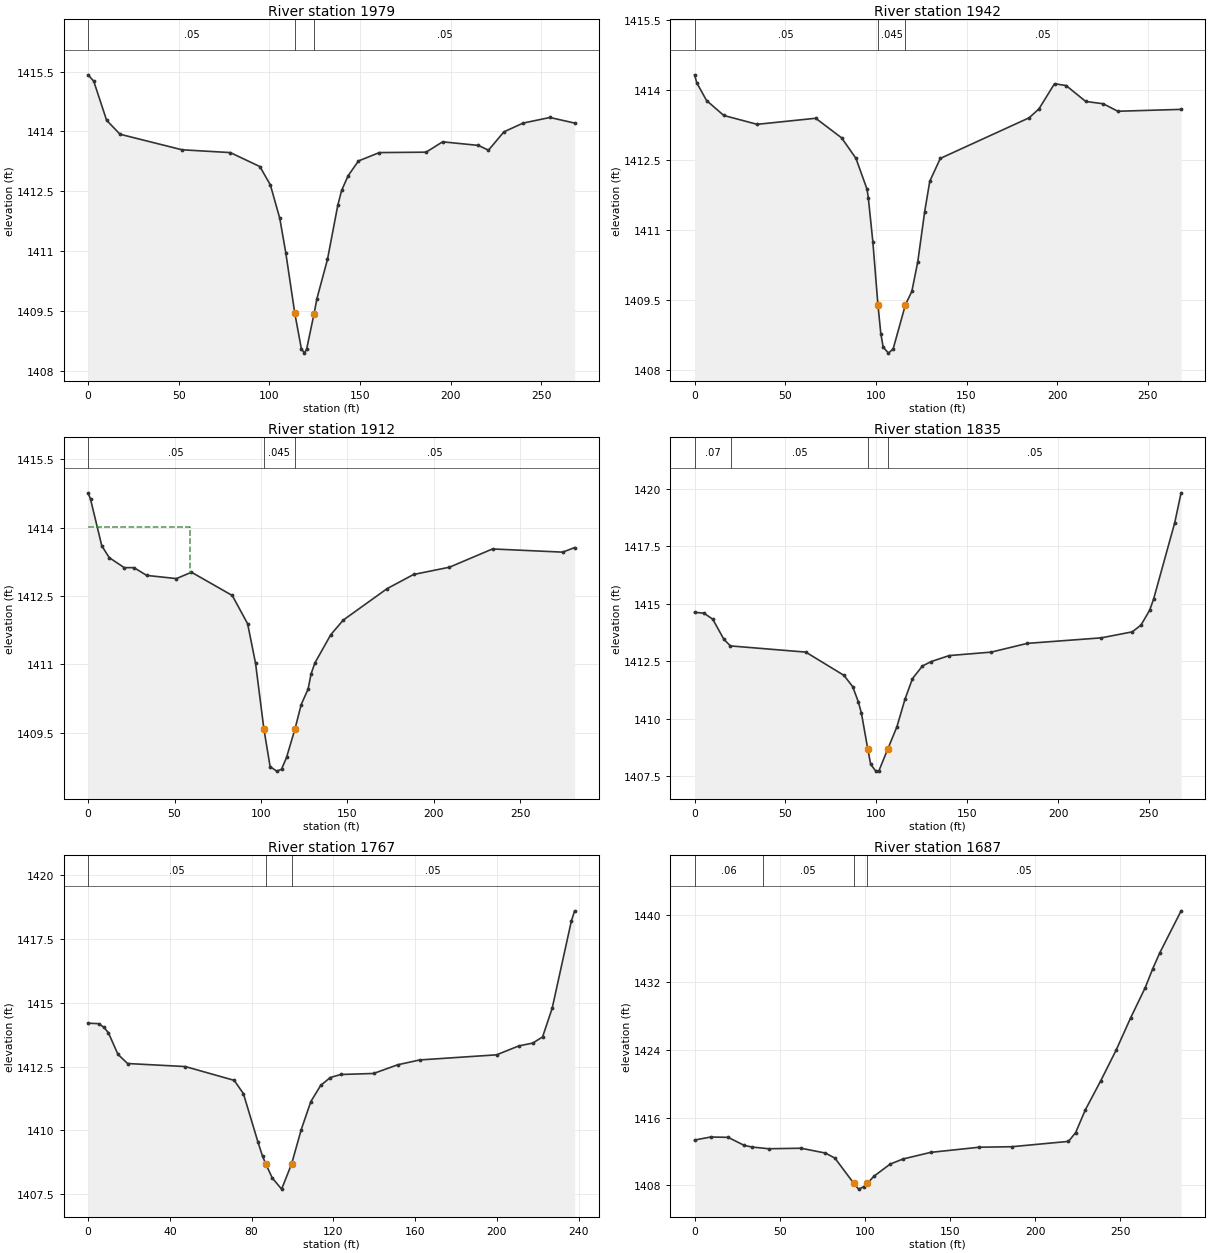
Type RM Length L Ch R = 1 ,1979    ,37.2,37.1,37.1
XS GIS Cut Line= 2
2203154.16949651753482.8948299152202996.78481621753700.130022451
#Sta/Elev= 30
       0 1415.42     3.1 1415.26    10.2 1414.28    17.6 1413.93    51.8 1413.54
    78.4 1413.47    94.7 1413.12   100.5 1412.66   105.7 1411.82     109 1410.96
     1141409.434   117.6 1408.55   119.3 1408.44   120.5 1408.54   124.61409.427
   126.2 1409.81     132 1410.79   137.7 1412.15   139.8 1412.52   143.4 1412.89
   149.1 1413.26   160.6 1413.47   186.4 1413.48   195.5 1413.74   215.2 1413.65
   220.8 1413.53   229.3 1413.99   239.9 1414.21   254.7 1414.35   268.3 1414.21
#Mann= 3 ,-1,0
       0     .05       0     114    .045       0   124.6     .05       0
Bank Sta=114,124.6
XS Rating Curve= 0 ,0
Exp/Cntr(USF)=0,0
Exp/Cntr=0.3,0.1

Type RM Length L Ch R = 1 ,1942    ,29.7,30,30
XS GIS Cut Line= 2
2203128.40052597753460.1738021242202971.01584566 753677.40899466
#Sta/Elev= 30
       0 1414.33     1.2 1414.16     6.6 1413.78    16.1 1413.46    34.5 1413.27
    66.8  1413.4    81.1 1412.98      89 1412.54    95.1 1411.88    95.8  1411.7
    98.3 1410.76   101.1 1409.41   102.7 1408.79     104  1408.5   106.9 1408.37
   109.5 1408.46   116.3 1409.41   119.8 1409.69   123.1 1410.33   126.9  1411.4
   129.7 1412.05   135.5 1412.54   184.5 1413.41   189.9  1413.6   198.5 1414.14
   204.9  1414.1   215.7 1413.76   225.4 1413.71   233.4 1413.55   268.3 1413.59
#Mann= 3 ,-1,0
       0     .05       0   101.1    .045       0   116.3     .05       0
Bank Sta=101.1,116.3
XS Rating Curve= 0 ,0
Exp/Cntr(USF)=0,0
Exp/Cntr=0.3,0.1

Type RM Length L Ch R = 1 ,1912    ,73.1,76.7,80.2
XS GIS Cut Line= 2
2203117.04001207753436.8986029242202943.58436089753658.567166736
#Sta/Elev= 30
       0 1414.76     1.4 1414.62     7.9  1413.6    12.2 1413.34    20.9 1413.12
    26.5 1413.12    33.9 1412.95    51.1 1412.88    59.8 1413.02    83.4 1412.51
    92.3 1411.89    96.9 1411.02   101.71409.586   105.3 1408.76   109.1 1408.66
   111.9  1408.7   114.8 1408.96  119.66 1409.58   123.3 1410.12   127.3 1410.46
     129 1410.79   131.2 1411.03   140.4 1411.65   147.6 1411.97     173 1412.66
   188.3 1412.97   209.1 1413.13     234 1413.53   274.6 1413.46   281.5 1413.56
#Mann= 3 ,-1,0
       0     .05       0   101.7    .045       0  119.66     .05       0
#XS Ineff= 2 , 0
           59.15 1414.02
Permanent Ineff=
       F       F
Bank Sta=101.7,119.66
XS Rating Curve= 0 ,0
Exp/Cntr(USF)=0,0
Exp/Cntr=0.3,0.1

Type RM Length L Ch R = 1 ,1835    ,68.2,68.5,68.8
XS GIS Cut Line= 2
2203096.53566992753399.2149470762202873.75876329 753547.73288483
#Sta/Elev= 30
       0 1414.63     5.2 1414.59      10 1414.33    16.1 1413.46    19.7 1413.17
    61.2  1412.9    82.2 1411.89      87  1411.4    90.1 1410.74    91.8 1410.25
    95.3 1408.69    96.9 1408.03    99.7 1407.73   101.4 1407.74   106.2 1408.67
   111.3 1409.65   115.8 1410.86   119.9 1411.75   125.4  1412.3   130.2 1412.49
   140.1 1412.75   163.2  1412.9   183.1 1413.28   223.8 1413.52   240.8 1413.78
   245.6 1414.07   250.4 1414.72   252.6 1415.21   264.2 1418.52   267.7 1419.82
#Mann= 4 ,-1,0
       0     .07       0      20     .05       0    95.3    .045       0
   106.2     .05       0
Bank Sta=95.3,106.2
XS Rating Curve= 0 ,0
Exp/Cntr(USF)=0,0
Exp/Cntr=0.3,0.1

Type RM Length L Ch R = 1 ,1767    ,80,79.8,79.7
XS GIS Cut Line= 2
2203056.54043269753346.9666265442202854.84200849753473.470462778
#Sta/Elev= 30
       0  1414.2     5.2 1414.18     7.7 1414.04     9.9 1413.83    14.6 1412.98
    19.3 1412.62    47.6  1412.5    71.5 1411.96      76 1411.44    83.1 1409.55
    85.4 1408.98      87 1408.68    90.1 1408.14    94.7  1407.7    99.6 1408.69
   104.3 1410.03     109 1411.13   113.8 1411.76   118.5 1412.07   123.7 1412.19
   139.7 1412.23   151.5 1412.57   162.3 1412.76   199.9 1412.96   210.8 1413.31
   217.6 1413.42   222.4 1413.66   227.1 1414.78   236.5  1418.2   238.1  1418.6
#Mann= 3 ,-1,0
       0     .05       0      87    .045       0    99.6     .05       0
Bank Sta=87,99.6
XS Rating Curve= 0 ,0
Exp/Cntr(USF)=0,0
Exp/Cntr=0.3,0.1

Type RM Length L Ch R = 1 ,1687    ,93.5,93.9,94.2
XS GIS Cut Line= 3
2203016.72257905753276.6119262862202812.28692347753408.182129524
2202772.33047914753422.488512517
#Sta/Elev= 30
       0 1413.35     9.5 1413.71    19.7 1413.67    29.2 1412.71    33.9 1412.52
    43.5 1412.32    62.5 1412.38    76.8 1411.81    82.4 1411.21    93.4 1408.24
    93.4 1408.22    96.3 1407.54    99.2 1407.81  101.381408.213   105.3 1409.07
   114.8  1410.5   122.4 1411.11   138.6 1411.89   167.1  1412.5   186.2 1412.56
   219.5 1413.19   223.7 1414.23   229.4 1416.93   238.5 1420.39   247.5 1424.01
     256 1427.82   264.5 1431.37     269 1433.65     273 1435.47   285.6 1440.48
#Mann= 4 ,-1,0
       0     .06       0      40     .05       0    93.4    .045       0
  101.38     .05       0
Bank Sta=93.4,101.38
XS Rating Curve= 0 ,0
Exp/Cntr=0.3,0.1

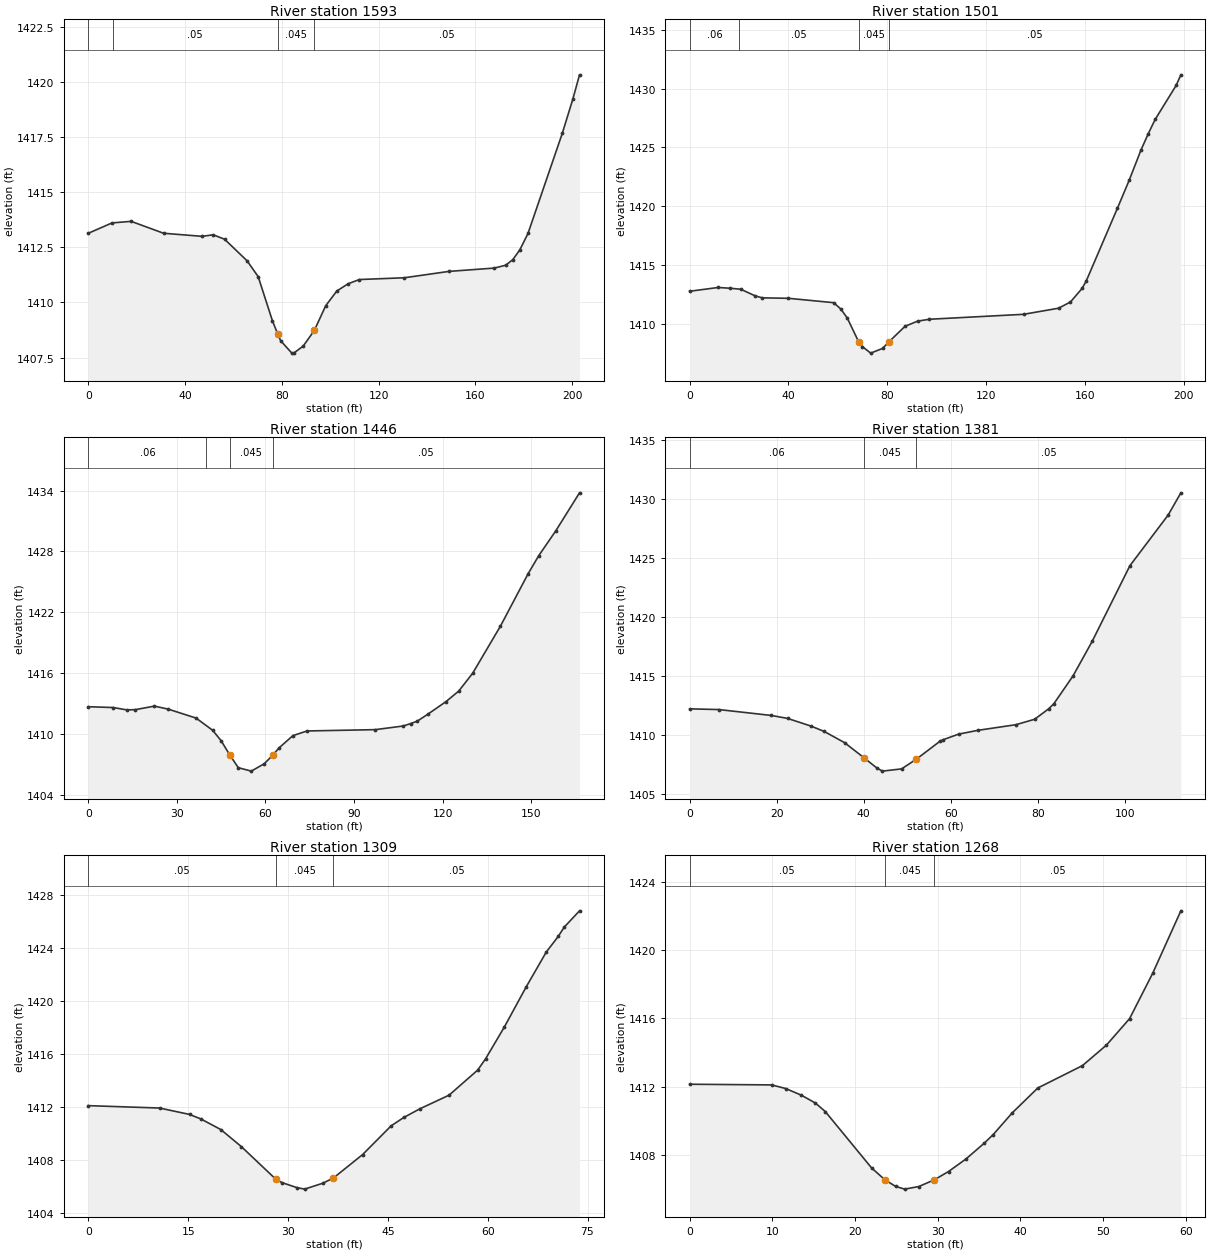
Type RM Length L Ch R = 1 ,1593    ,92.5,92.1,91.6
XS GIS Cut Line= 2
 2202960.6301187753205.3795808852202785.86108806753308.564248426
#Sta/Elev= 30
       0 1413.14     9.8 1413.61    17.7 1413.68    31.1 1413.14      47    1413
    51.6 1413.07    56.3 1412.87    65.6 1411.89    70.2 1411.17    76.1 1409.16
    78.3 1408.56    79.5 1408.26    84.1  1407.7    84.9  1407.7    88.8 1408.02
    93.4 1408.73    98.1 1409.85   102.7 1410.52   107.4 1410.85     112 1411.04
   130.6 1411.12   149.1 1411.41   167.8 1411.56   172.5 1411.69   175.4 1411.94
   178.3 1412.38   181.7 1413.13   195.9 1417.68   200.3 1419.25     203 1420.33
#Mann= 4 ,-1,0
       0     .06       0      10     .05       0    78.3    .045       0
    93.4     .05       0
Bank Sta=78.3,93.4
XS Rating Curve= 0 ,0
Exp/Cntr(USF)=0,0
Exp/Cntr=0.3,0.1

Type RM Length L Ch R = 1 ,1501    ,54.3,54.5,54.8
XS GIS Cut Line= 2
2202901.80565658753130.2158413752202734.55061718753237.937800034
#Sta/Elev= 30
       0 1412.77    11.5 1413.09    16.2 1413.03    20.7 1412.94    26.5 1412.38
    29.4 1412.21      40 1412.17    58.3  1411.8    61.2 1411.26    63.8  1410.5
    68.5 1408.44    69.9 1408.07    73.3 1407.51    78.1 1407.9180.565921408.447
    87.2 1409.79    92.3 1410.23    97.1 1410.39   135.2 1410.81   149.4 1411.33
   154.2 1411.86   158.9 1413.01   160.6 1413.65   173.2 1419.82     178 1422.22
   182.7 1424.75   185.6 1426.12   188.5 1427.38     197 1430.27   198.9 1431.17
#Mann= 4 ,-1,0
       0     .06       0      20     .05       0    68.5    .045       0
80.56592     .05       0
Bank Sta=68.5,80.56592
XS Rating Curve= 0 ,0
Exp/Cntr=0.3,0.1

Type RM Length L Ch R = 1 ,1446    ,63.6,64.9,66.5
XS GIS Cut Line= 3
2202859.31667605753094.4725806642202756.39080812753157.170223559
 2202717.4441815753181.423353135
#Sta/Elev= 30
       0 1412.69     8.4 1412.61      13 1412.38    15.9  1412.4    22.4 1412.75
    27.1 1412.45    36.5 1411.57    42.1 1410.37      45 1409.33    47.9 1407.94
    50.8 1406.68    55.2 1406.34    59.6 1407.07    62.5 1407.92    64.6 1408.63
    69.3 1409.84    74.1  1410.3    97.2 1410.43   106.7 1410.79   109.2 1411.03
   111.4 1411.26   114.9 1411.93   121.2  1413.2   125.5 1414.24   130.2 1415.99
   139.6 1420.63     149 1425.81   152.6 1427.59   158.4 1430.05   166.4 1433.78
#Mann= 4 ,-1,0
       0     .06       0      40     .05       0    47.9    .045       0
    62.5     .05       0
Bank Sta=47.9,62.5
XS Rating Curve= 0 ,0
Exp/Cntr=0.3,0.1

Type RM Length L Ch R = 1 ,1381    ,72.5,72.7,72.9
XS GIS Cut Line= 2
2202820.72899515753048.9445318952202717.50208502753094.635386969
#Sta/Elev= 25
       0 1412.22     6.7 1412.16    18.8 1411.66    22.5 1411.41    27.9 1410.76
    30.9 1410.31    35.6 1409.36      40  1408.1      43 1407.22    44.3 1406.95
    48.7 1407.14    52.1 1407.96    57.5 1409.47    58.2  1409.6    61.8 1410.08
    66.2  1410.4      75 1410.88    79.3 1411.34    82.5 1412.22    83.7 1412.65
    88.1    1415    92.5 1417.92   101.2 1424.34     110 1428.63   112.9  1430.5
#Mann= 3 ,-1,0
       0     .06       0      40    .045       0    52.1     .05       0
Bank Sta=40,52.1
XS Rating Curve= 0 ,0
Exp/Cntr(USF)=0,0
Exp/Cntr=0.3,0.1

Type RM Length L Ch R = 1 ,1309    ,43.2,40.3,37.5
XS GIS Cut Line= 2
 2202778.1621132752989.104132626 2202710.0956351753017.541785233
#Sta/Elev= 25
       0 1412.12    10.7 1411.94    15.2 1411.46    16.9 1411.12    19.9 1410.32
      23 1409.03    28.2 1406.56    29.1 1406.32    31.3 1405.95    32.5 1405.83
    35.2 1406.27    36.8 1406.66    41.2 1408.43    45.5  1410.6    47.4 1411.23
    49.8 1411.88    54.2 1412.91    58.5  1414.8    59.7 1415.66    62.5 1418.04
    65.8 1421.08    68.8 1423.69    70.6 1424.87    71.5 1425.57    73.8  1426.8
#Mann= 3 ,-1,0
       0     .05       0    28.2    .045       0    36.8     .05       0
Bank Sta=28.2,36.8
XS Rating Curve= 0 ,0
Exp/Cntr(USF)=0,0
Exp/Cntr=0.3,0.1

Type RM Length L Ch R = 1 ,1268    ,32.8,32,31.2
XS GIS Cut Line= 2
2202747.52941725752949.4228994712202703.27231682752989.027177287
#Sta/Elev= 23
       0 1412.14     9.9  1412.1    11.6 1411.89    13.5  1411.5    15.2 1411.04
    16.4 1410.54      22 1407.24    23.6 1406.55    24.9 1406.16      26    1406
    27.7 1406.15    29.6 1406.55    31.3 1407.03    33.4 1407.76    35.6 1408.68
    36.7 1409.19      39 1410.46    42.1 1411.92    47.5 1413.23    50.4 1414.43
    53.2 1415.98      56 1418.64    59.4 1422.29
#Mann= 3 ,-1,0
       0     .05       0    23.6    .045       0    29.6     .05       0
Bank Sta=23.6,29.6
XS Rating Curve= 0 ,0
Exp/Cntr(USF)=0,0
Exp/Cntr=0.3,0.1

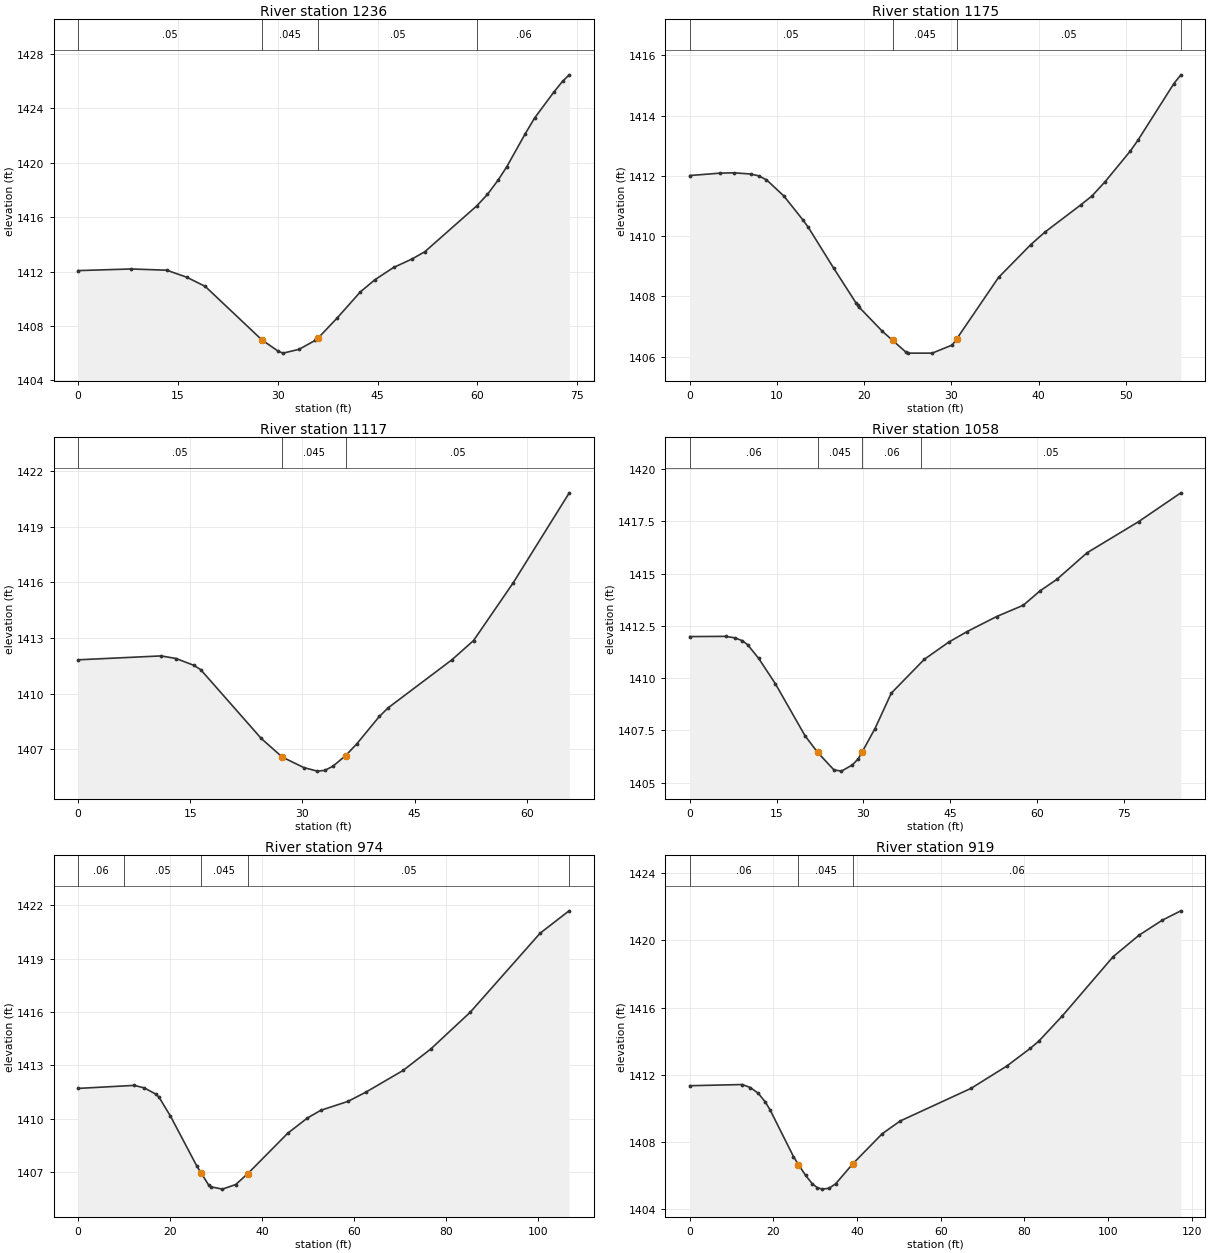
Type RM Length L Ch R = 1 ,1236    ,60.4,61.2,62
XS GIS Cut Line= 2
2202729.33928335752919.3582826222202678.56468807752972.953688751
#Sta/Elev= 26
       0 1412.07       8 1412.19    13.3  1412.1    16.3 1411.59    19.1 1410.91
    27.6 1406.98    30.1 1406.13    30.8    1406    33.2 1406.28    35.6 1406.93
    36.1 1407.13    38.9 1408.57    42.4  1410.5    44.6  1411.4    47.4  1412.3
    50.2 1412.93    52.1 1413.46    59.9 1416.83    61.5 1417.67    63.1 1418.72
    64.4  1419.7    67.2 1422.15    68.6  1423.3    71.5 1425.21    72.8    1426
    73.8 1426.47
#Mann= 4 ,-1,0
       0     .05       0    27.6    .045       0    36.1     .05       0
      60     .06       0
Bank Sta=27.6,36.1
XS Rating Curve= 0 ,0
Exp/Cntr(USF)=0,0
Exp/Cntr=0.3,0.1

Type RM Length L Ch R = 1 ,1175    ,58.2,58.5,58.5
XS GIS Cut Line= 2
2202690.78820175752876.5759847482202648.47603902752913.716660924
#Sta/Elev= 30
       0 1412.01     3.5 1412.09     5.1  1412.1       7 1412.06     7.9    1412
     8.8 1411.87    10.8 1411.33      13 1410.53    13.6 1410.29    16.5 1408.94
    19.1 1407.77    19.3  1407.7    19.4 1407.65    22.1 1406.84   23.251406.546
    24.8 1406.15      25 1406.12    27.8 1406.12    30.1 1406.39    30.6 1406.59
    35.4 1408.63    39.1 1409.72    40.7 1410.13    44.8 1411.03    46.1 1411.33
    47.6  1411.8    50.5 1412.82    51.4 1413.19    55.5 1415.06    56.3 1415.35
#Mann= 4 ,-1,0
       0     .05       0   23.25    .045       0    30.6     .05       0
    56.3     .06       0
Bank Sta=23.25,30.6
XS Rating Curve= 0 ,0
Exp/Cntr(USF)=0,0
Exp/Cntr=0.3,0.1

Type RM Length L Ch R = 1 ,1117    ,57.8,58.4,59
XS GIS Cut Line= 2
2202660.69955269752827.2117948922202610.39509256752869.523957625
#Sta/Elev= 19
       0 1411.83    11.1 1412.04    13.1  1411.9    15.5 1411.53    16.4  1411.3
    24.5 1407.59    27.3 1406.59    30.2 1406.02      32 1405.83      33 1405.87
    34.1  1406.1    35.8 1406.67    37.3 1407.31    40.3 1408.78    41.5 1409.25
      50 1411.83    52.9 1412.87    58.2 1415.98    65.7 1420.83
#Mann= 3 ,-1,0
       0     .05       0    27.3    .045       0    35.8     .05       0
Bank Sta=27.3,35.8
XS Rating Curve= 0 ,0
Exp/Cntr(USF)=0,0
Exp/Cntr=0.3,0.1

Type RM Length L Ch R = 1 ,1058    ,85.3,84.4,83.4
XS GIS Cut Line= 3
2202624.23193089752784.5695312982202586.89740122752811.993910235
2202562.43121047752841.626940045
#Sta/Elev= 26
       0 1411.99     6.2    1412     7.8 1411.93     9.1 1411.79      10  1411.6
    11.9 1410.95    14.8 1409.73    19.9 1407.25   22.071406.453    24.9 1405.61
    26.2 1405.55    28.1 1405.85    29.1 1406.14    29.8 1406.48      32 1407.59
    34.8 1409.28    40.5  1410.9    44.7 1411.72    47.9 1412.23      53 1412.95
    57.6 1413.49    60.5 1414.18    63.4 1414.73    68.6    1416    77.5 1417.49
    84.8 1418.87
#Mann= 4 ,-1,0
       0     .06       0   22.07    .045       0    29.8     .06       0
      40     .05       0
Bank Sta=22.07,29.8
XS Rating Curve= 0 ,0
Exp/Cntr=0.3,0.1

Type RM Length L Ch R = 1 ,974     ,55,54.8,54.6
XS GIS Cut Line= 2
2202573.22935132752713.8255897772202493.90613815752785.409952883
#Sta/Elev= 23
       0  1411.7    12.2 1411.87    14.4 1411.73    16.9 1411.38    17.6 1411.21
    20.1 1410.14    25.8 1407.35   26.741406.959    28.4 1406.27    28.9 1406.17
    31.4 1406.04    34.3  1406.3   36.921406.911    45.6 1409.18    49.9 1410.04
    52.8 1410.47    58.7 1410.97    62.6 1411.49    70.7 1412.71    76.7 1413.91
    85.3 1415.98   100.5 1420.42   106.8 1421.68
#Mann= 5 ,-1,0
       0     .06       0      10     .05       0   26.74    .045       0
   36.92     .05       0  106.85     .06       0
Bank Sta=26.74,36.92
XS Rating Curve= 0 ,0
Exp/Cntr(USF)=0,0
Exp/Cntr=0.3,0.1

Type RM Length L Ch R = 1 ,919     ,37.9,38.1,38.7
XS GIS Cut Line= 2
2202537.17857999752671.0515980732202453.01858553752752.889937516
#Sta/Elev= 26
       0 1411.36    12.6 1411.43    14.5 1411.25    16.4 1410.91    18.1 1410.38
    19.2 1409.93    24.8 1407.15      26 1406.67    27.7 1406.03    29.3 1405.53
    30.5  1405.3    31.7 1405.21    33.3 1405.26    34.9 1405.53      39 1406.72
      46  1408.5    50.3 1409.26    67.3 1411.21    75.8 1412.53    81.4 1413.58
    83.4    1414    89.1 1415.52   101.2 1419.03   107.4 1420.31     113 1421.21
   117.4 1421.76
#Mann= 3 ,-1,0
       0     .06       0      26    .045       0      39     .06       0
Bank Sta=26,39
XS Rating Curve= 0 ,0
Exp/Cntr(USF)=0,0
Exp/Cntr=0.3,0.1

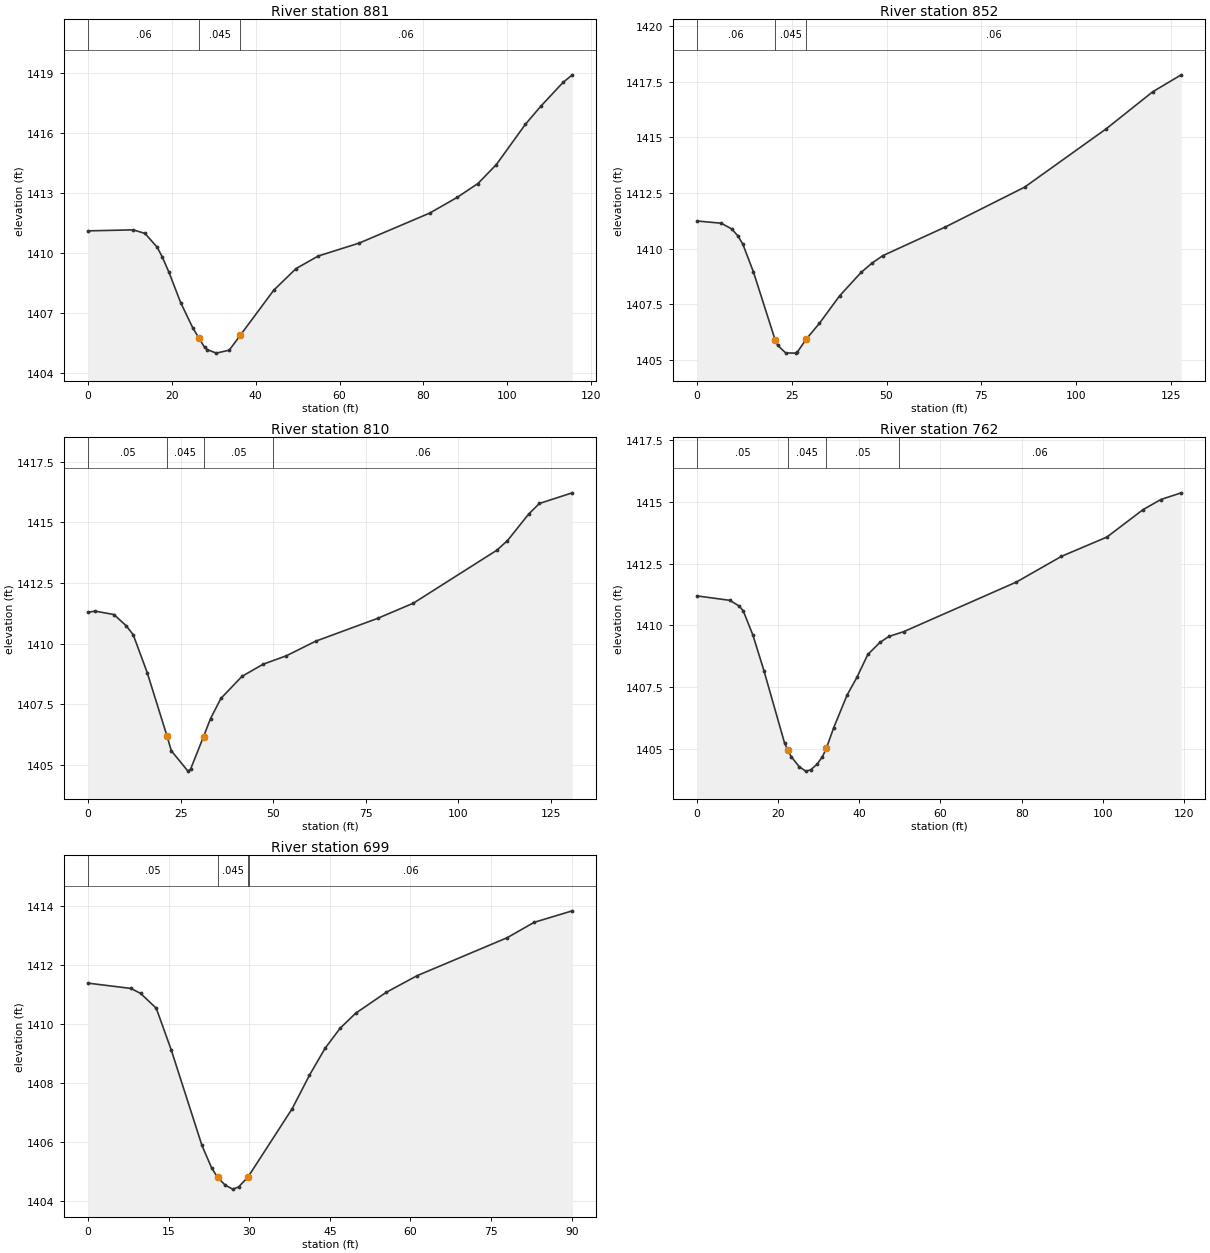
Type RM Length L Ch R = 1 ,881     ,28.5,28.6,28.8
XS GIS Cut Line= 2
 2202513.5473471752643.325144477 2202426.5424358752719.246627583
#Sta/Elev= 26
       0 1411.12    10.8 1411.17    13.6 1410.99    16.5  1410.3    17.7 1409.82
    19.3 1409.05    22.1 1407.53      25 1406.26    26.51405.742    27.8 1405.29
    28.4 1405.18    30.6    1405    33.7 1405.15    36.3 1405.89    44.3 1408.15
    49.6 1409.23    54.9 1409.86    64.7 1410.51    81.5 1412.01      88 1412.79
      93 1413.49    97.4 1414.44   104.3 1416.45     108 1417.36   113.3 1418.55
   115.5 1418.93
#Mann= 3 ,-1,0
       0     .06       0    26.5    .045       0    36.3     .06       0
Bank Sta=26.5,36.3
XS Rating Curve= 0 ,0
Exp/Cntr(USF)=0,0
Exp/Cntr=0.3,0.1

Type RM Length L Ch R = 1 ,852     ,42.3,42.4,42.5
XS GIS Cut Line= 3
2202492.48883353752624.483316553 2202455.3593491752655.516915487
2202389.96712277752700.404799659
#Sta/Elev= 22
       0 1411.24     6.4 1411.14     9.2 1410.88    10.8 1410.57    12.1  1410.2
    14.9 1408.95    20.6 1405.91    21.3 1405.65    23.4 1405.31      26  1405.3
    26.5 1405.35    28.81405.925    32.3 1406.64    37.6 1407.87    43.3 1408.93
    46.2 1409.35      49 1409.68    65.5 1410.97    86.4 1412.76   107.9 1415.38
   120.2 1417.05   127.7 1417.81
#Mann= 3 ,-1,0
       0     .06       0    20.6    .045       0    28.8     .06       0
Bank Sta=20.6,28.8
XS Rating Curve= 0 ,0
Exp/Cntr(USF)=0,0
Exp/Cntr=0.3,0.1

Type RM Length L Ch R = 1 ,810     ,47.2,47.3,47.5
XS GIS Cut Line= 3
2202465.61152017752592.0642890952202419.61529318752629.747944943
2202360.87312377752670.202457839
#Sta/Elev= 24
       0 1411.29     1.9 1411.34       7  1411.2    10.3 1410.74    12.2 1410.37
      16  1408.8    21.31406.208    22.5 1405.58      27 1404.74    27.7 1404.82
    31.21406.163    33.1 1406.91    35.9 1407.74    41.6 1408.65    47.3 1409.15
    53.6  1409.5    61.5  1410.1    78.2 1411.04    87.9 1411.67   110.4 1413.85
   113.3 1414.25     119 1415.34   121.9 1415.78   130.8 1416.22
#Mann= 4 ,-1,0
       0     .05       0    21.3    .045       0    31.2     .05       0
      50     .06       0
Bank Sta=21.3,31.2
XS Rating Curve= 0 ,0
Exp/Cntr(USF)=0,0
Exp/Cntr=0.3,0.1

Type RM Length L Ch R = 1 ,762     ,62.8,63,63.3
XS GIS Cut Line= 3
2202437.07169258752554.6577189522202398.27969391752585.691317886
2202335.65832464 752616.17074541
#Sta/Elev= 28
       0 1411.19     8.1 1411.01    10.4 1410.78    11.4 1410.59    13.8  1409.6
    16.5 1408.17    21.6 1405.23    22.4 1404.95    23.2 1404.69    25.2 1404.28
    26.8  1404.1      28 1404.15    29.6 1404.38    30.9 1404.68    31.9 1405.03
    33.7 1405.86      37 1407.18    39.4 1407.89    42.1 1408.82    45.1 1409.31
    47.3 1409.55    50.9 1409.74    78.7 1411.75    89.8 1412.79     101 1413.57
   109.9 1414.68   114.3 1415.09   119.3 1415.36
#Mann= 4 ,-1,0
       0     .05       0    22.4    .045       0    31.9     .05       0
   49.68     .06       0
Bank Sta=22.4,31.9
XS Rating Curve= 0 ,0
Exp/Cntr(USF)=0,0
Exp/Cntr=0.3,0.1

Type RM Length L Ch R = 1 ,699     ,79,78.5,78
XS GIS Cut Line= 2
 2202398.5752198752505.8570242332202326.53703525752559.917509771
#Sta/Elev= 22
       0 1411.37       8 1411.19     9.8 1411.02    12.7 1410.52    15.5  1409.1
    21.2 1405.87      23 1405.11    24.1 1404.79    25.5 1404.53    26.9 1404.39
      28 1404.46    29.8 1404.81      38 1407.12    41.2 1408.25    44.1 1409.16
    46.9 1409.84    49.8 1410.35    55.5 1411.06    61.2 1411.62      78 1412.91
      83 1413.43    90.1 1413.82
#Mann= 4 ,-1,0
       0     .05       0    24.1    .045       0    29.8     .05       0
      30     .06       0
Bank Sta=24.1,29.8
XS Rating Curve= 0 ,0
Exp/Cntr(USF)=0,0
Exp/Cntr=0.3,0.1