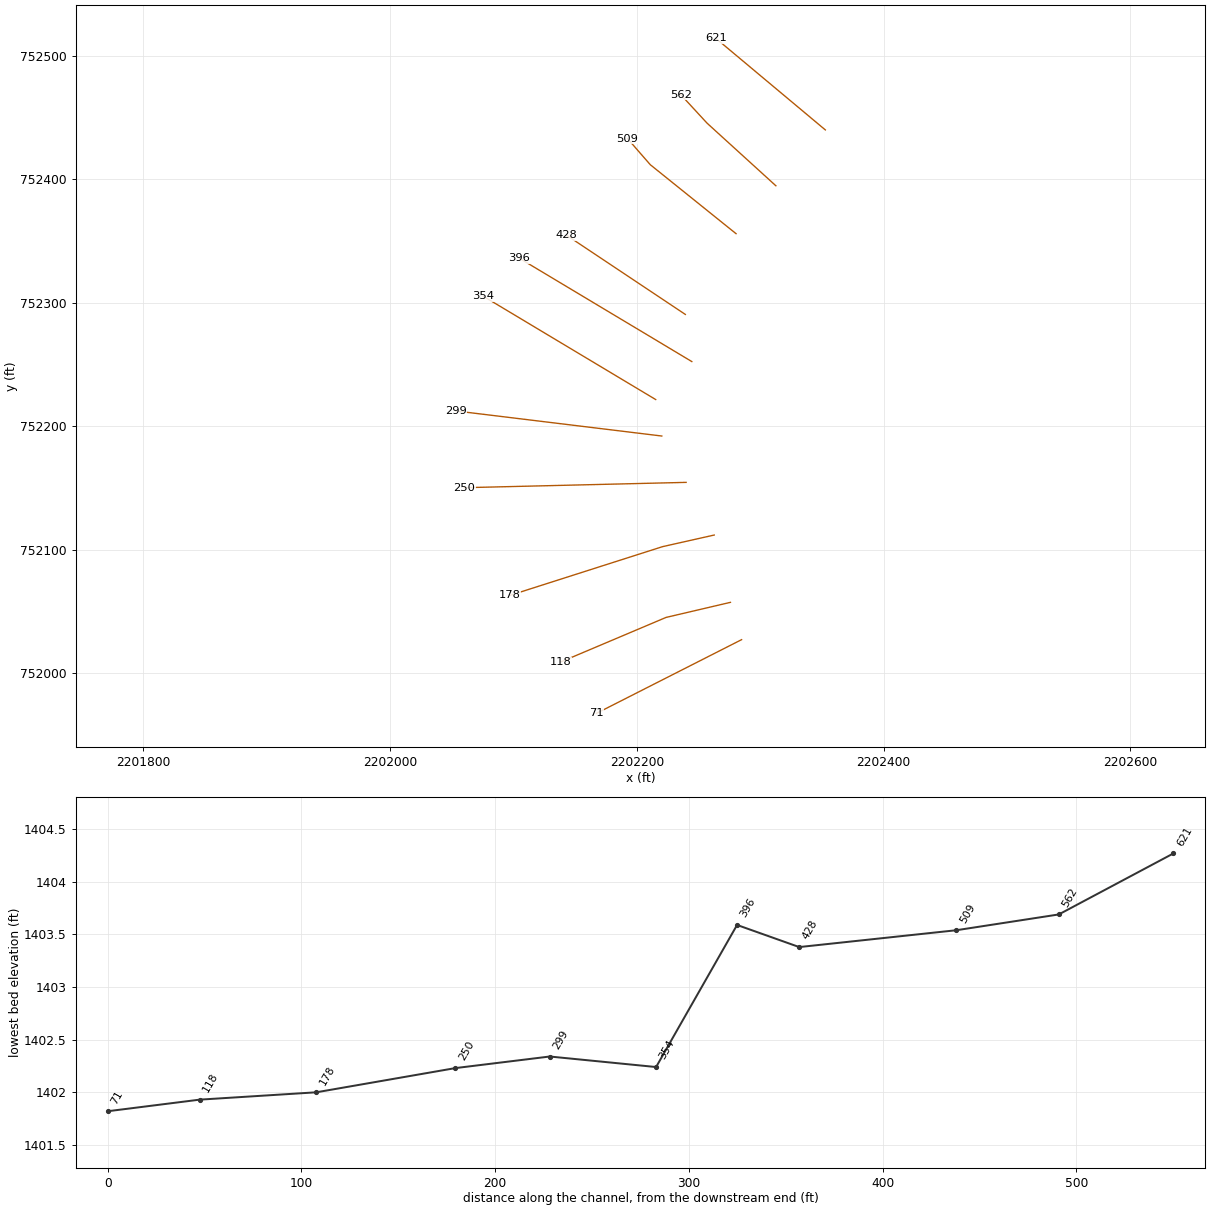
HEC-RAS study PECKSRNT3.prj: PECKSRNT3

--- PECKSRNT3.g01 (geometry) --- (continued)

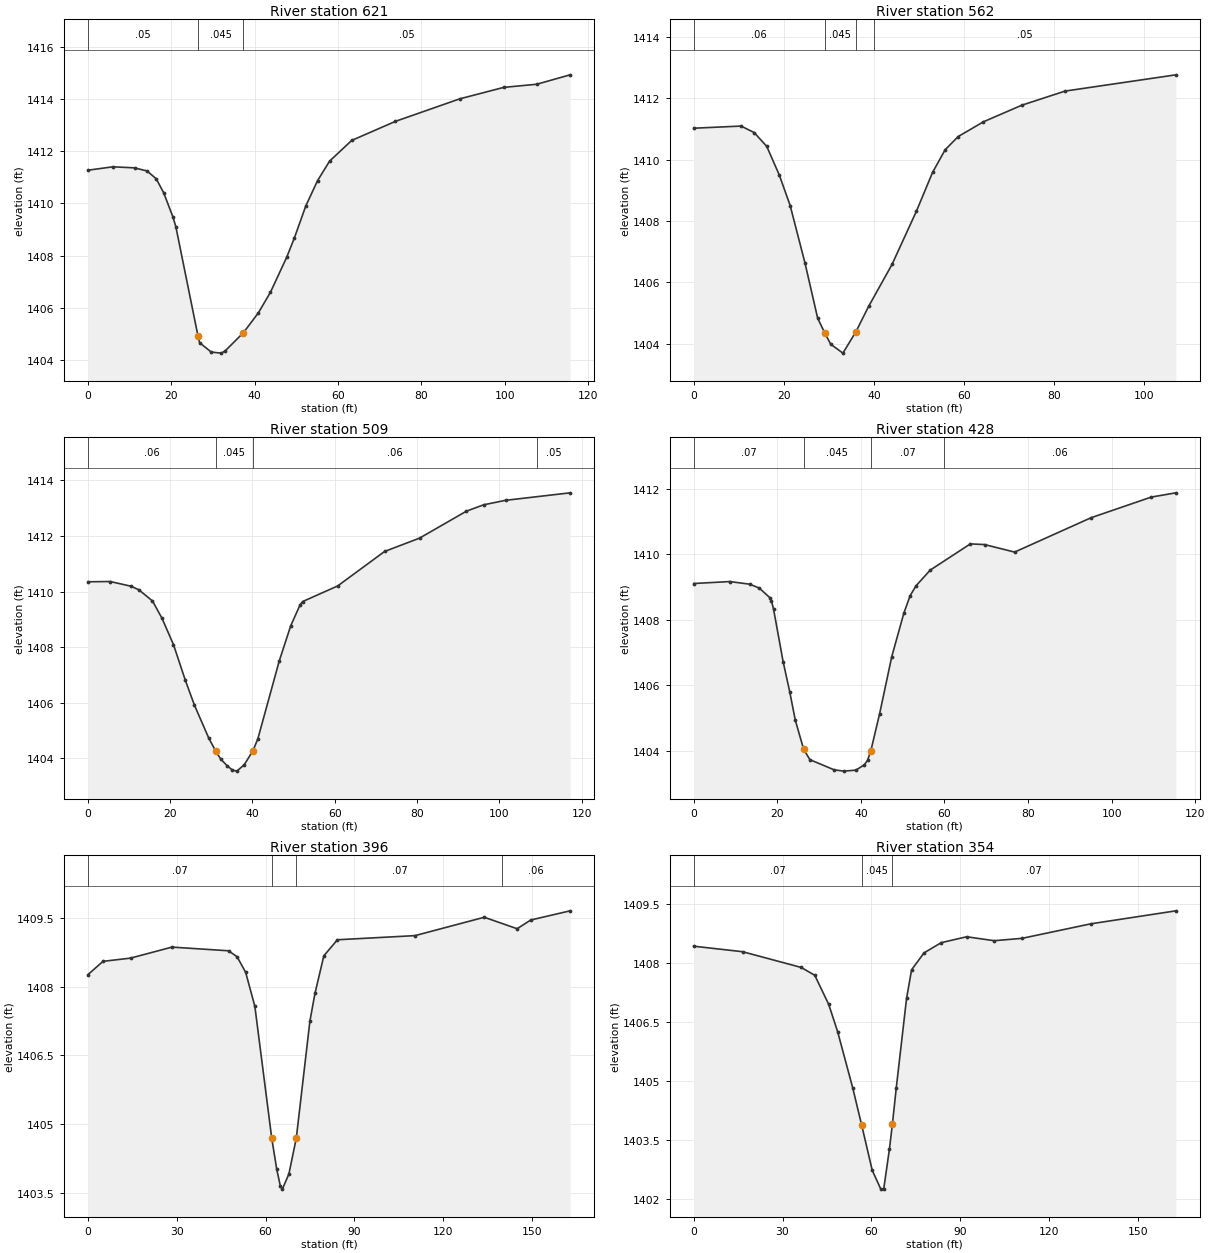
Type RM Length L Ch R = 1 ,621     ,59.6,59.2,58.8
XS GIS Cut Line= 2
2202352.75500941752440.0865905922202264.00462897752514.299040175
#Sta/Elev= 27
       0 1411.27       6  1411.4    11.2 1411.36    14.2 1411.24    16.4 1410.94
    18.2  1410.4    20.4 1409.48    21.1 1409.11    26.41404.936    26.8 1404.67
    29.6 1404.31      32 1404.27    32.9 1404.35    37.3 1405.05    40.9 1405.81
    43.8  1406.6    47.7 1407.94    49.5 1408.66    52.3 1409.91    55.1 1410.87
      58 1411.62    63.3 1412.41    73.8 1413.14    89.2    1414    99.8 1414.44
   107.7 1414.56   115.7 1414.92
#Mann= 3 ,-1,0
       0     .05       0    26.4    .045       0    37.3     .05       0
Bank Sta=26.4,37.3
XS Rating Curve= 0 ,0
Exp/Cntr(USF)=0,0
Exp/Cntr=0.3,0.1

Type RM Length L Ch R = 1 ,562     ,52.2,52.9,53.4
XS GIS Cut Line= 3
2202312.67946349  752394.80222492202256.78776857752445.677998479
2202235.50593089752468.751236636
#Sta/Elev= 22
       0 1411.02    10.5 1411.09    13.4 1410.88    16.2 1410.43      19 1409.49
    21.4  1408.5    24.7 1406.62    27.5 1404.83   29.071404.349    30.4 1403.98
    33.1 1403.69      36 1404.39    38.8 1405.21      44 1406.58    49.4 1408.31
      53 1409.58    55.8 1410.32    58.7 1410.75    64.3 1411.23    72.8 1411.77
    82.4 1412.23     107 1412.76
#Mann= 4 ,-1,0
       0     .06       0   29.07    .045       0      36     .06       0
      40     .05       0
Bank Sta=29.07,36
XS Rating Curve= 0 ,0
Exp/Cntr(USF)=0,0
Exp/Cntr=0.3,0.1

Type RM Length L Ch R = 1 ,509     ,81.4,81.1,81.9
XS GIS Cut Line= 3
2202280.38188725752356.018947624 2202210.8755487752411.910642542
2202192.45995178752433.049168182
#Sta/Elev= 29
       0 1410.35     5.4 1410.36    10.5 1410.19    12.4 1410.06    15.7 1409.66
      18 1409.04    20.8 1408.09    23.7  1406.8    25.9 1405.91    29.4 1404.72
    31.1 1404.25    32.3 1403.97    33.8 1403.74    35.1 1403.58    36.2 1403.54
      38 1403.77    40.1 1404.27    41.3  1404.7    46.5  1407.5    49.3 1408.77
    51.6 1409.53    52.2 1409.64    60.7  1410.2    72.1 1411.44    80.6 1411.92
      92 1412.89    96.2 1413.12   101.5 1413.28   117.2 1413.55
#Mann= 4 ,-1,0
       0     .06       0    31.1    .045       0    40.1     .06       0
  109.19     .05       0
Bank Sta=31.1,40.1
XS Rating Curve= 0 ,0
Exp/Cntr(USF)=0,0
Exp/Cntr=0.3,0.1

Type RM Length L Ch R = 1 ,428     ,31.8,32.1,32.5
XS GIS Cut Line= 2
2202239.29691406752290.5627986972202143.24053641752354.600383798
#Sta/Elev= 30
       0 1409.11     8.6 1409.17    13.4 1409.09    15.7 1408.97    18.2 1408.68
    18.6 1408.58    19.1 1408.33    21.4 1406.72      23 1405.79    24.3 1404.94
    26.3 1404.05    27.8 1403.73    33.6 1403.42    35.9 1403.38    38.8 1403.41
    40.8 1403.57    41.6 1403.71    42.41404.008    44.5 1405.14    47.4 1406.88
    50.3 1408.21    51.8 1408.74    53.2 1409.04    56.6 1409.52    66.2 1410.32
    69.6  1410.3    76.8 1410.07    95.1 1411.12   109.5 1411.75   115.4 1411.88
#Mann= 4 ,-1,0
       0     .07       0    26.3    .045       0    42.4     .07       0
      60     .06       0
Bank Sta=26.3,42.4
XS Rating Curve= 0 ,0
Exp/Cntr(USF)=0,0
Exp/Cntr=0.3,0.1

Type RM Length L Ch R = 1 ,396     ,43.3,41.8,41.8
XS GIS Cut Line= 2
2202244.53075515 752252.386546042202104.75641075 752336.12800348
#Sta/Elev= 23
       0 1408.26     5.1 1408.55    14.4 1408.62    28.4 1408.86    47.5 1408.78
    50.4 1408.65    53.3 1408.31    56.4 1407.57    62.1  1404.7    63.8 1404.02
      65 1403.66    65.7 1403.59    67.9 1403.92    70.4  1404.7      75 1407.25
    76.7 1407.85    79.7 1408.67    84.3 1409.02   110.5 1409.11   133.9 1409.51
     145 1409.26   149.6 1409.45   162.9 1409.65
#Mann= 4 ,-1,0
       0     .07       0    62.1    .045       0    70.4     .07       0
     140     .06       0
Bank Sta=62.1,70.4
XS Rating Curve= 0 ,0
Exp/Cntr(USF)=0,0
Exp/Cntr=0.3,0.1

Type RM Length L Ch R = 1 ,354     ,50.7,54.9,58.4
XS GIS Cut Line= 2
2202215.28281965752221.5992455112202075.50847525752305.340702951
#Sta/Elev= 23
       0 1408.42    16.5 1408.28    36.3 1407.88    40.9 1407.68    45.6 1406.94
    48.6 1406.25    53.7 1404.82    56.7 1403.88    60.3 1402.72    63.2 1402.24
    64.2 1402.25    66.1 1403.25   67.13  1403.9    68.4  1404.8    71.9 1407.09
    73.6 1407.82    77.8 1408.25    83.6 1408.51    92.2 1408.66   101.5 1408.56
   110.9 1408.62   134.2 1408.99   162.9 1409.32
#Mann= 3 ,-1,0
       0     .07       0    56.7    .045       0   67.13     .07       0
Bank Sta=56.7,67.13
XS Rating Curve= 0 ,0
Exp/Cntr(USF)=0,0
Exp/Cntr=0.3,0.1

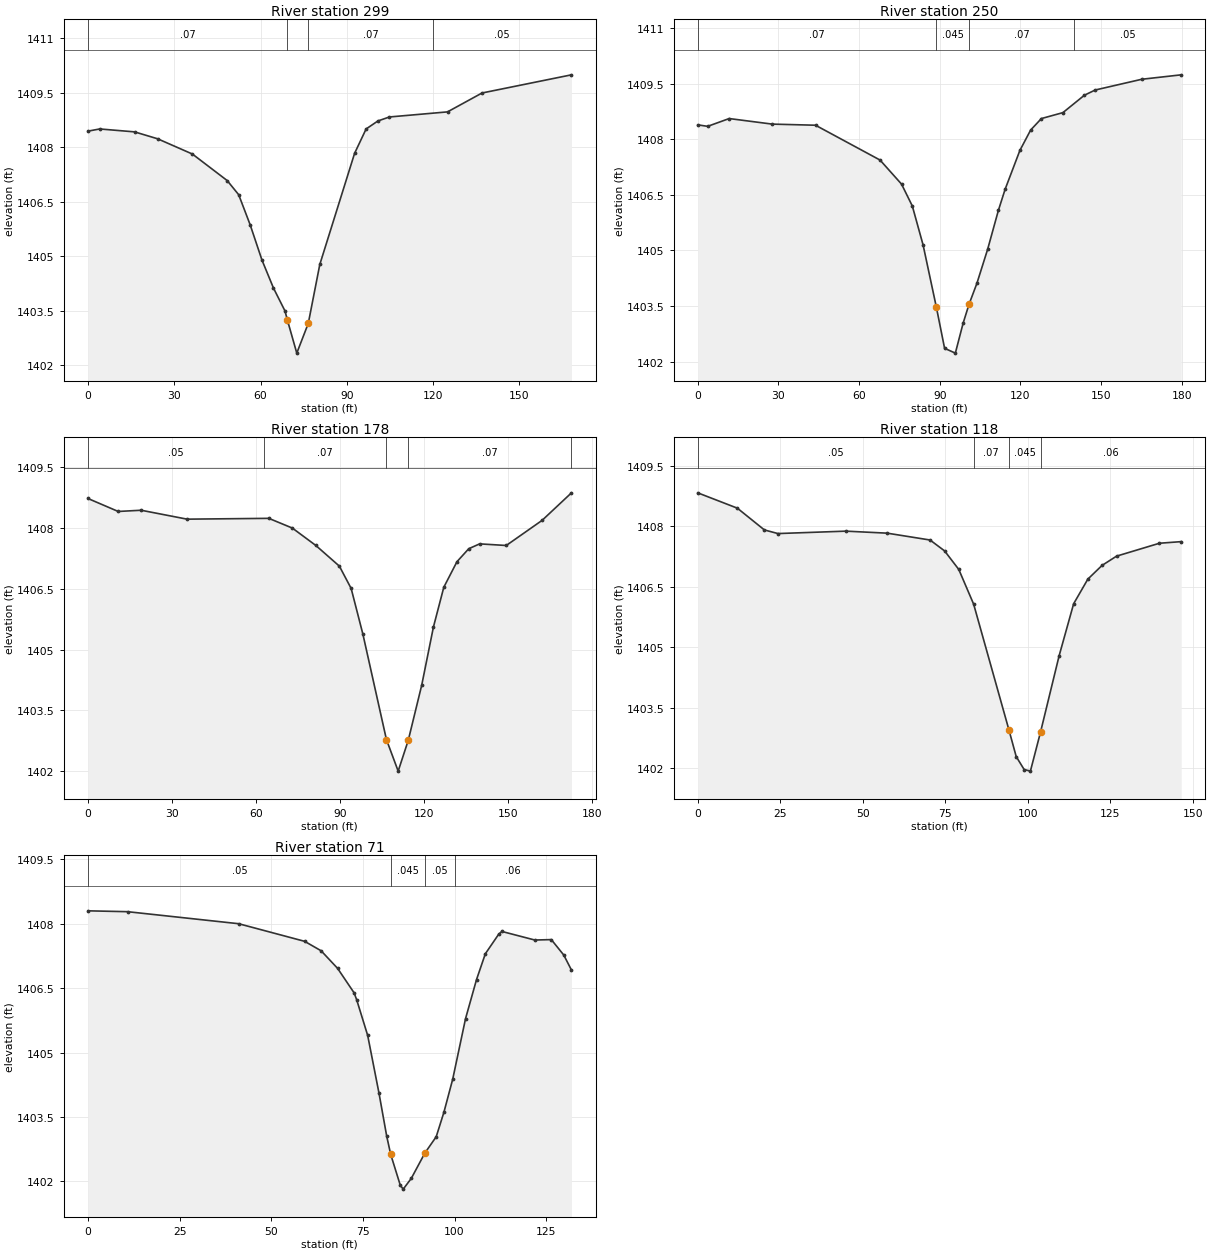
Type RM Length L Ch R = 1 ,299     ,47.2,48.7,50.1
XS GIS Cut Line= 2
2202220.20878774752192.0434370032202053.34161887752212.363055352
#Sta/Elev= 22
       0 1408.45     4.1 1408.51    16.2 1408.43    24.2 1408.24    36.3 1407.82
    48.4 1407.09    52.4  1406.7    56.4 1405.87    60.5  1404.9    64.5 1404.13
    68.5  1403.5    69.3 1403.26    72.6 1402.34    76.6 1403.16    80.6 1404.78
    92.7 1407.84    96.7 1408.51   100.8 1408.73   104.8 1408.84     125 1408.98
     137  1409.5   168.1    1410
#Mann= 4 ,-1,0
       0     .07       0    69.3    .045       0    76.6     .07       0
     120     .05       0
Bank Sta=69.3,76.6
XS Rating Curve= 0 ,0
Exp/Cntr(USF)=0,0
Exp/Cntr=0.3,0.1

Type RM Length L Ch R = 1 ,250     ,69,71.8,74.4
XS GIS Cut Line= 2
2202239.91266007752154.4829303572202060.11482498752150.172708283
#Sta/Elev= 26
       0 1408.39     3.7 1408.35    11.7 1408.56    27.7 1408.41    43.8 1408.38
    67.8 1407.44    75.8 1406.79    79.8  1406.2    83.8 1405.15    88.71403.484
    91.8 1402.36    95.8 1402.23    98.7 1403.04   100.9 1403.55   103.8 1404.11
   107.8 1405.03   111.8 1406.08   114.3 1406.65   119.8  1407.7   123.8 1408.25
   127.8 1408.56   135.8 1408.72   143.8 1409.19   147.8 1409.33   165.1 1409.62
   179.8 1409.74
#Mann= 4 ,-1,0
       0     .07       0    88.7    .045       0   100.9     .07       0
     140     .05       0
Bank Sta=88.7,100.9
XS Rating Curve= 0 ,0
Exp/Cntr(USF)=0,0
Exp/Cntr=0.3,0.1

Type RM Length L Ch R = 1 ,178     ,59.5,60.3,61
XS GIS Cut Line= 3
2202262.69285474752111.8051536162202220.85082715752102.402450786
2202097.20528494752062.911098902
#Sta/Elev= 22
       0 1408.73    10.8 1408.41      19 1408.44    35.4 1408.22    64.6 1408.24
      73    1408    81.4 1407.57    89.8 1407.06      94 1406.51    98.2 1405.38
   106.6 1402.78   110.8    1402   114.4 1402.76   119.2 1404.12   123.4 1405.56
   127.1 1406.54   131.8 1407.17     136 1407.49   139.9 1407.61   149.4 1407.57
   162.2 1408.19   172.7 1408.87
#Mann= 5 ,-1,0
       0     .05       0   62.89     .07       0   106.6    .045       0
   114.4     .07       0  172.68     .05       0
Bank Sta=106.6,114.4
XS Rating Curve= 0 ,0
Exp/Cntr(USF)=0,0
Exp/Cntr=0.3,0.1

Type RM Length L Ch R = 1 ,118     ,46.6,47.4,47.9
XS GIS Cut Line= 3
2202275.85663871752057.269477204  2202223.671638752045.045963526
2202138.10704225752008.845557632
#Sta/Elev= 22
       0 1408.83      12 1408.45    20.2 1407.91    24.3 1407.82    44.9 1407.88
    57.4 1407.83    70.4 1407.66    74.8 1407.39    79.1 1406.93    83.6 1406.07
    94.3 1402.95    96.5 1402.29    98.9 1401.97   100.8 1401.93  103.871402.899
   109.5 1404.79   113.9 1406.08   118.2 1406.69   122.5 1407.03   126.9 1407.26
   139.9 1407.58   146.5 1407.62
#Mann= 4 ,-1,0
       0     .05       0    83.6     .07       0    94.3    .045       0
  103.87     .06       0
Bank Sta=94.3,103.87
XS Rating Curve= 0 ,0
Exp/Cntr(USF)=0,0
Exp/Cntr=0.3,0.1

Type RM Length L Ch R = 1 ,71      ,,,
XS GIS Cut Line= 2
2202284.86211885752027.0235061652202167.25463083751967.296143138
#Sta/Elev= 28
       0  1408.3    10.8 1408.28    41.1    1408    59.1 1407.59    63.6 1407.37
    68.1 1406.96    72.6 1406.39    73.3 1406.23    76.3  1405.4    79.4 1404.05
    81.5 1403.05   82.58 1402.63    85.2 1401.91      86 1401.82    88.2 1402.07
    91.91402.659      95 1403.04    97.1 1403.61    99.5 1404.38     103 1405.79
     106  1406.7   108.4  1407.3     112 1407.75   112.9 1407.82   121.9 1407.62
   126.4 1407.63   129.8 1407.27   131.9 1406.92
#Mann= 4 ,-1,0
       0     .05       0   82.58    .045       0    91.9     .05       0
     100     .06       0
Bank Sta=82.58,91.9
XS Rating Curve= 0 ,0
Exp/Cntr(USF)=0,0
Exp/Cntr=0.3,0.1
LCMann Table=0

Chan Stop Cuts=-1
Use User Specified Reach Order=0
Composite Channel Slope=5